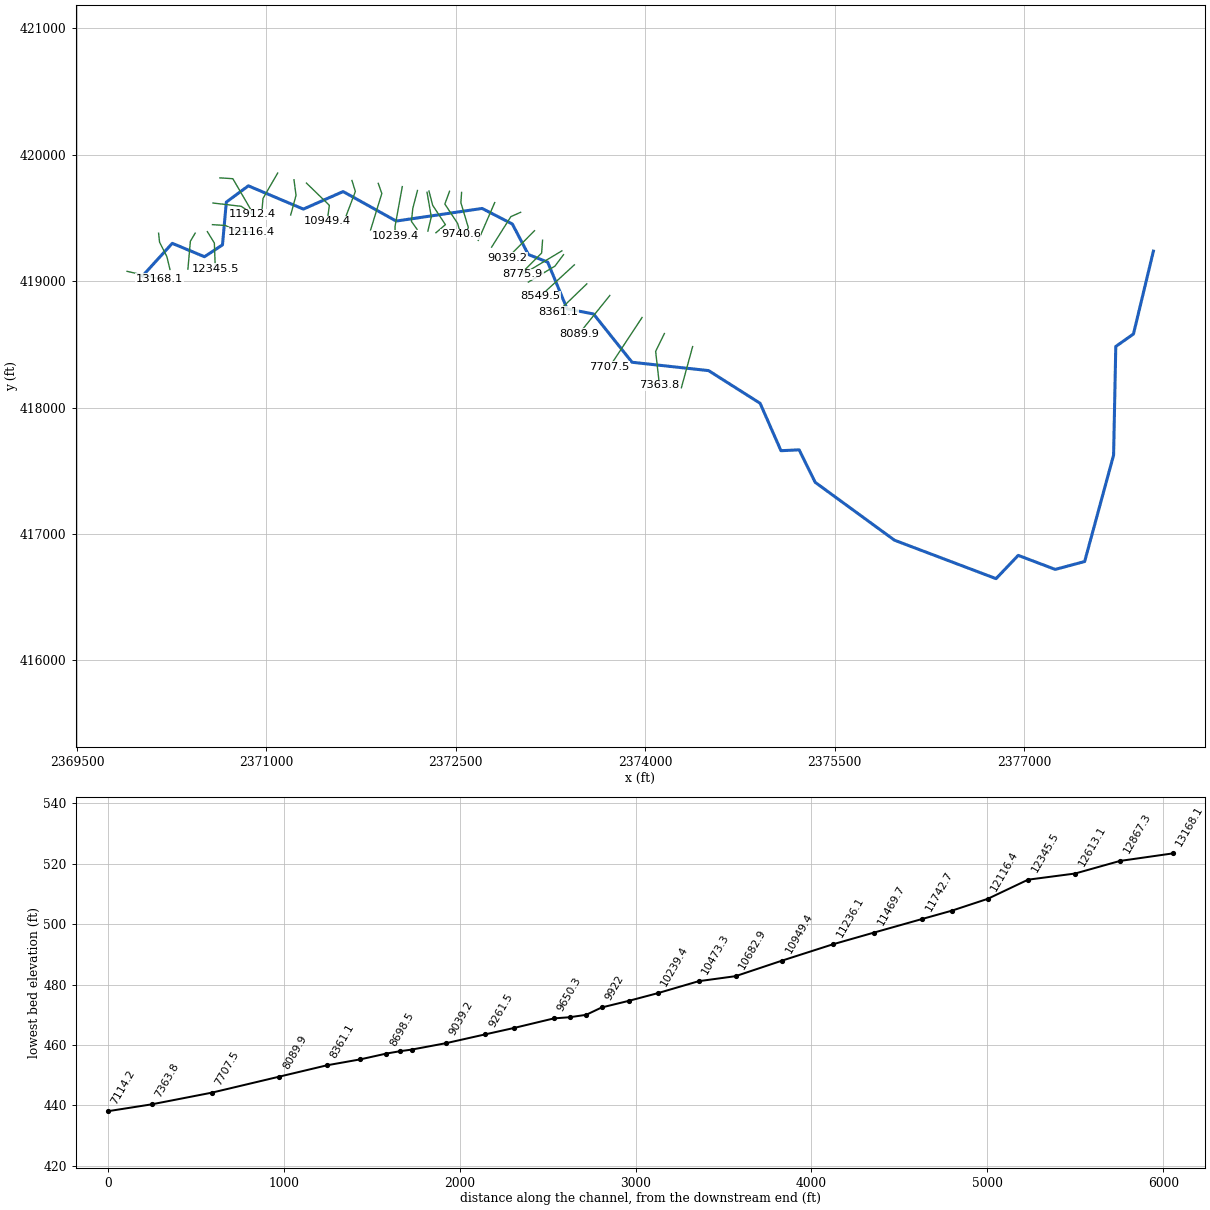
--- BIGRUN2.prj (project) ---

Proj Title=BIGRUN2
Current Plan=p01
Default Exp/Contr=0,0
English Units
Geom File=g01
Flow File=f01
Plan File=p01
BEGIN DESCRIPTION:
END DESCRIPTION:
DSS Export Rating Curves= 0
DSS Export Rating Curve Sorted= 0
DSS Export Volume Flow Curves= 0
DXF OffsetX= 0
DXF OffsetY= 0
DXF ScaleX= 0
DXF ScaleY= 0

--- BIGRUN2.p01 (plan) ---

Plan Title=Floodplain
Program Version=4.00
Geom File=g01
Flow File=f01
K Sum by GR=0
Std Step Tol=0.01
Critical Tol=0.01
Num of Std Step Trials=20
Max Error Tol=0.3
Flow Tol Ratio=0.001
Split Flow NTrial=30
Split Flow Tol=0.02
Split Flow Ratio=0.02
Log Output Level=0
Friction Slope Method=1
Unsteady Friction Slope Method=2
Unsteady Bridges Friction Slope Method=1
Global Log Level=0
CheckData=False
Run HTab=0
Run UNet=0
Run PostProcess=0
UNET Theta=0
UNET Theta Warmup=0
UNET ZTol=0
UNET ZSATol=0
UNET MxIter=0
UNET MaxInSteps=0
UNET DtIC=0
UNET DtMin=0
UNET MaxCRTS=0
UNET WFStab=0
UNET SFStab=0
UNET WFX=0
UNET SFX=0
UNET DSS MLevel=0
UNET DZMax Abort=0
UNET Convert EG Bridges=0
UNET Use Existing IB Tables=0
UNET Froude Limit=0
UNET Froude Power=0
Write IC File=0
Echo Input=False
Echo Output=False
Write Detailed=0

--- BIGRUN2.f01 (steady flow) ---

Flow Title=NFF Regression Equation
Program Version=5.03
Number of Profiles= 1
Profile Names=P100yr
River Rch & RM=BIGRUN2,Main            ,13168.1
512.1093
River Rch & RM=BIGRUN2,Main            ,12613.1
 543.886
River Rch & RM=BIGRUN2,Main            ,11469.7
581.5239
River Rch & RM=BIGRUN2,Main            ,10682.9
641.1736
River Rch & RM=BIGRUN2,Main            ,7707.5
707.0119
River Rch & RM=BIGRUN2,Main            ,7363.8
800.7233
River Rch & RM=BIGRUN2,Main            ,5599
821.9627
River Rch & RM=BIGRUN2,Main            ,3786.7
910.9582
River Rch & RM=BIGRUN2,Main            ,196.1
1012.129
Boundary for River Rch & Prof#=BIGRUN2,Main            , 1
Up Type= 0
Dn Type= 3
Dn Slope=0.00987
DSS Import GetInterval= 0
DSS Import GetPeak= 0
DSS Import FillOption= 0

--- BIGRUN2.g01 (geometry) ---

Geom Title=USGS 10m DEM
Program Version=4.10

River Reach=BIGRUN2         ,Main
Reach XY= 30
     2370018.671       419040.25     2370254.782      419298.931
      2370509.99      419193.028     2370652.351      419286.778
     2370682.834      419625.218     2370857.212      419753.792
     2371292.976      419569.764     2371607.212      419708.653
     2372027.669      419475.262     2372707.907      419574.972
      2372947.49      419451.708     2373074.226      419210.389
     2373227.105      419150.305     2373380.968      418780.108
     2373589.952      418740.236     2373895.407      418357.959
      2374501.31      418291.986     2374909.296      418033.306
     2375074.226      417658.306     2375218.323       417665.25
      2375345.06      417408.306     2375973.532      416949.972
     2376777.351      416646.153     2376952.698      416830.181
     2377246.101      416719.069      2377478.74       416781.57
     2377707.907      417623.583     2377725.268      418482.958
     2377865.227      418581.594     2378023.092      419237.038

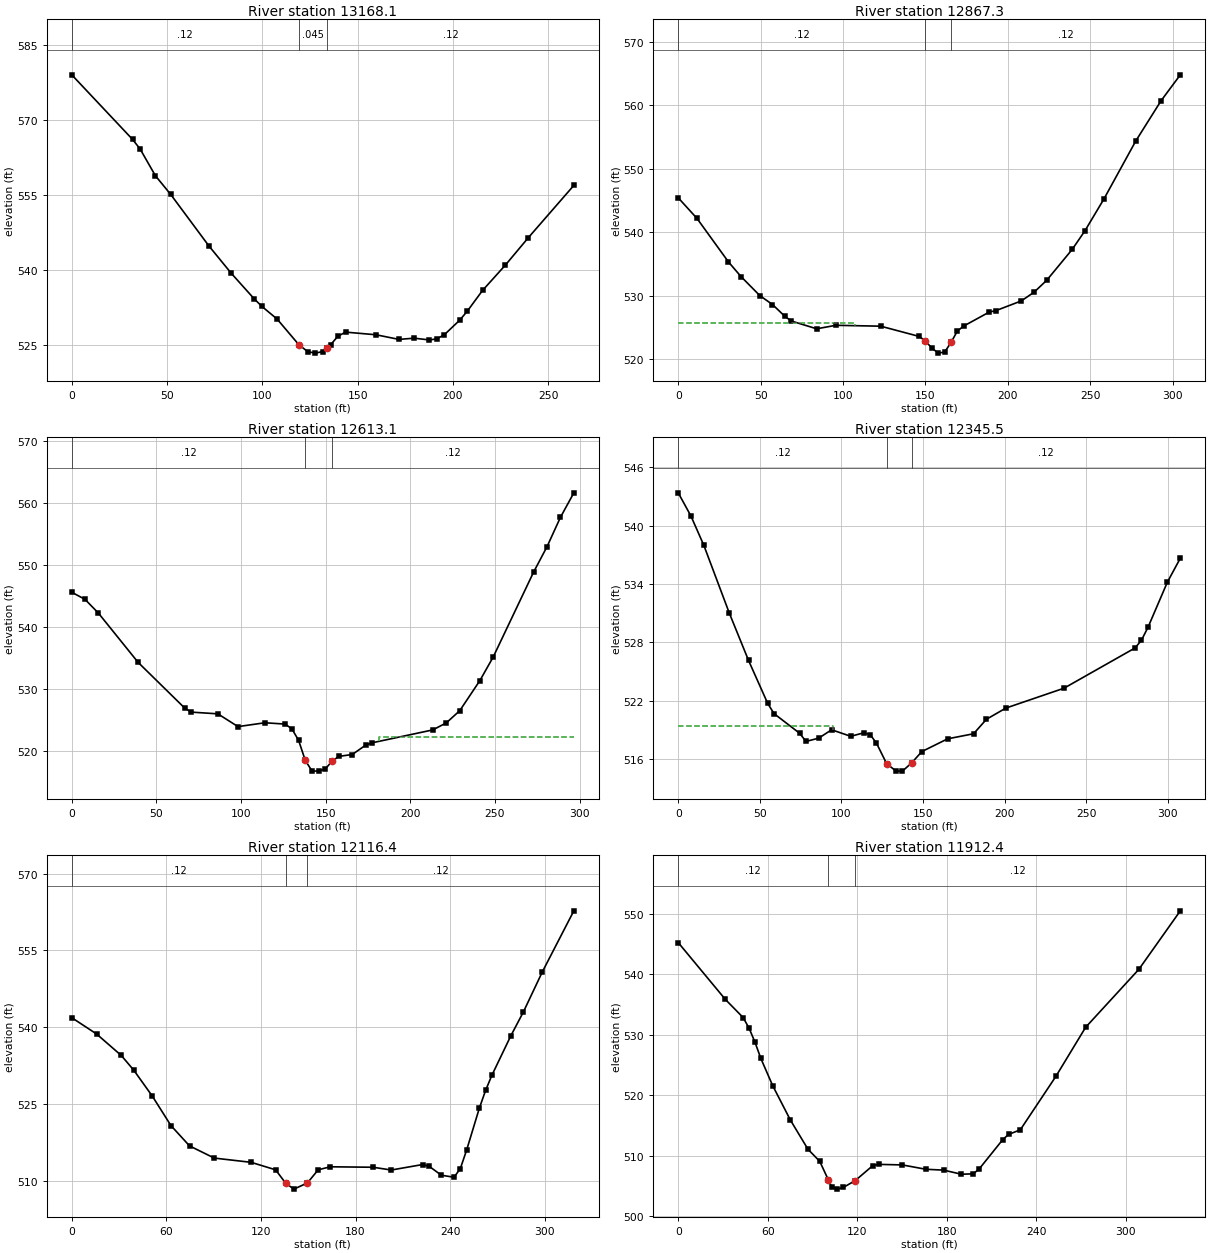
Type RM Length L Ch R = 1 ,13168.1 ,313.4,300.8,280.2
XS GIS Cut Line= 2
     2369897.214      419077.485     2370153.985      419018.241
#Sta/Elev= 30
       0  578.96    31.9  566.08    35.9  564.15    43.9  558.83    51.9  555.12
    71.9  544.87    83.8  539.34    95.8  534.26    99.8  532.77   107.8  530.24
   119.1  525.17   123.8  523.76   127.8  523.46   131.8  523.78   134.1  524.54
   135.8  525.11   139.7  526.84   143.7  527.65   159.7  527.12   171.7   526.2
   179.7  526.44   187.7  526.09   191.6   526.3   195.6  527.15   203.6  530.03
   207.6  531.84   215.6  535.97   227.6  541.03   239.6  546.48   263.5  556.91
#Mann= 3 ,-1 , 0
       0     .12       0   119.1    .045       0   134.1     .12       0
Bank Sta=119.1,134.1
XS Rating Curve= 0 ,0
Exp/Cntr=0.3,0.1

Type RM Length L Ch R = 1 ,12867.3 ,267.6,254.2,230.4
XS GIS Cut Line= 4
      2370146.39       419379.57     2370154.367      419307.605
     2370212.336      419193.383     2370236.451      419092.026
#Sta/Elev= 30
       0  545.41    11.4  542.16    30.5  535.31    38.1  533.01    49.5  530.02
    57.2  528.61    64.8  526.73    68.6  526.02      84  524.79    95.7  525.34
   122.9   525.2   146.2  523.59     150  522.87   153.9  521.76   157.8  520.96
   161.7  521.13   165.6  522.66   169.4  524.44   173.3  525.23   188.8  527.43
   192.7  527.64   208.2  529.18   215.9  530.54   223.6  532.42   239.1  537.29
   246.8  540.21   258.4  545.25   277.7  554.37   293.1  560.72   304.7  564.77
#Mann= 3 ,-1 , 0
       0     .12       0     150    .045       0   165.6     .12       0
#XS Ineff= 2 , 0
          107.28  525.74
Permanent Ineff=
       F       F
Bank Sta=150,165.6
XS Rating Curve= 0 ,0
Exp/Cntr=0.3,0.1

Type RM Length L Ch R = 1 ,12613.1 ,264.5,267.6,269.7
XS GIS Cut Line= 3
     2370436.103       419379.57     2370398.126       419315.55
     2370378.595      419094.196
#Sta/Elev= 30
       0  545.65     7.8  544.51    15.7   542.3    39.2  534.34    66.6     527
    70.5  526.32    86.3  526.04    98.2  523.98   114.1   524.6     126  524.39
     130  523.63     134  521.77   137.9  518.56   141.9  516.82   145.9   516.8
   149.8  517.16   153.8  518.41   157.8  519.18   165.7  519.48   173.6  520.99
   177.6  521.38   213.3  523.45   221.3  524.59   229.2  526.55   241.1  531.41
     249  535.23   272.8  548.89   280.8  553.03   288.7  557.75   296.6  561.69
#Mann= 3 ,-1 , 0
       0     .12       0   137.9    .045       0   153.8     .12       0
#XS Ineff= 2 , 0
                          181.42          522.26
Permanent Ineff=
       F       F
Bank Sta=137.9,153.8
XS Rating Curve= 0 ,0
Exp/Cntr=0.3,0.1

Type RM Length L Ch R = 1 ,12345.5 ,204.8,229.1,253
XS GIS Cut Line= 3
     2370532.675      419391.505     2370588.013      419301.445
     2370595.609      419099.622
#Sta/Elev= 30
       0  543.36     7.8  540.97    15.7  537.96    31.3     531    43.1  526.13
    54.8  521.73    58.7  520.67    74.4  518.65    78.3  517.81    86.1  518.15
      94  519.01   105.7  518.34   113.6  518.69   117.6  518.52   121.5  517.63
  127.69515.5399   133.4  514.77   137.4  514.76  143.14515.6201   149.3  516.77
   165.1  518.08     181   518.6   188.9  520.09   200.8  521.24   236.4  523.28
     280  527.42   283.9  528.22   287.9  529.54   299.8  534.19   307.7  536.64
#Mann= 3 ,-1 , 0
       0     .12       0  127.69    .045       0  143.14     .12       0
#XS Ineff= 2 , 0
           94.63   519.4
Permanent Ineff=
       F       F
Bank Sta=127.69,143.14
XS Rating Curve= 0 ,0
Exp/Cntr=0.3,0.1

Type RM Length L Ch R = 1 ,12116.4 ,195.2,204,211.2
XS GIS Cut Line= 4
     2370572.822      419446.844     2370674.819      419440.333
      2370769.22      419395.846     2370880.805      419387.444
#Sta/Elev= 30
       0  541.88    15.7  538.71    31.4  534.51    39.3  531.65    51.1  526.57
    62.9  520.83    74.7  516.86    90.4  514.48   113.8  513.65   129.3  512.19
  135.68 509.588   140.9  508.42   149.5  509.63   156.3  512.19     164  512.78
   191.1  512.69   202.7  512.15   222.6  513.22   226.6   512.9   234.5  511.13
   242.5  510.74   246.5  512.44   250.5  516.06   258.5  524.17   262.5  527.68
   266.5  530.64   278.5  538.33   286.5  543.01   298.5  550.82   318.5  562.74
#Mann= 3 ,-1 , 0
       0     .12       0  135.68    .045       0   149.5     .12       0
Bank Sta=135.68,149.5
XS Rating Curve= 0 ,0
Exp/Cntr=0.3,0.1

Type RM Length L Ch R = 1 ,11912.4 ,190.4,169.8,148.5
XS GIS Cut Line= 3
     2370577.379      419617.851     2370801.338      419591.809
     2370892.484      419528.007
#Sta/Elev= 30
       0  545.24    31.6  535.85    43.5  532.86    47.5   531.1    51.4  528.82
    55.4   526.1    63.3  521.62    75.2  515.92      87  511.09    94.9  509.09
  100.73505.9922   102.8  504.92   106.8   504.5   110.8  504.79   118.7  505.91
   130.5  508.39   134.5  508.59   150.3   508.5   166.1  507.78     178  507.64
   189.9  506.96   197.8  507.03   201.7   507.8   217.6  512.67   221.5  513.54
   229.4   514.3   253.3  523.15   273.2  531.24   308.9  540.82   336.7  550.49
#Mann= 3 ,-1 , 0
       0     .12       0  100.73    .045       0   118.7     .12       0
Bank Sta=100.73,118.7
XS Rating Curve= 0 ,0
Exp/Cntr=0.3,0.1

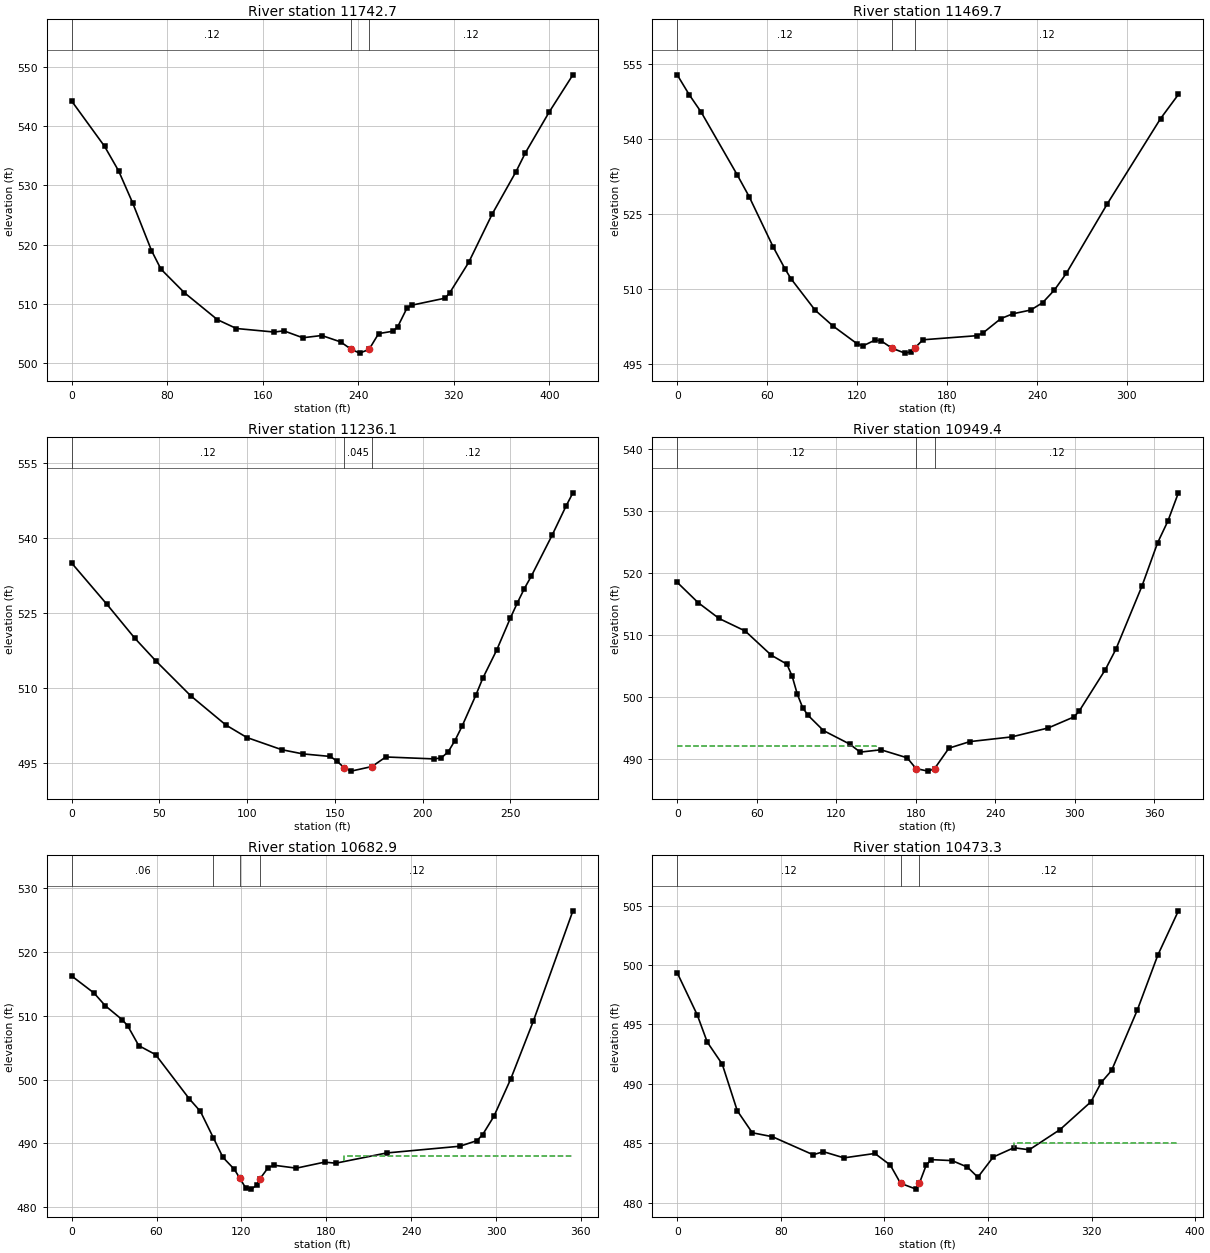
Type RM Length L Ch R = 1 ,11742.7 ,297.6,273,244.1
XS GIS Cut Line= 3
     2370632.501      419816.853     2370734.497      419810.342
     2370894.003       419535.82
#Sta/Elev= 30
       0   544.2    27.5  536.58    39.3  532.43    51.1  527.01    66.8  519.02
    74.7  515.89    94.3  511.92     122  507.37   137.9  505.88   169.7  505.28
   177.6  505.49   193.5  504.32   209.4   504.7   225.2  503.62  233.93502.3879
   241.1  501.73     249  502.36     257  505.02   268.9  505.42   272.9  506.14
   280.8  509.35   284.8  509.81   312.6  510.99   316.5  511.88   332.4  517.01
   352.2   525.2   372.1  532.33     380  535.52   399.9  542.38   419.7  548.63
#Mann= 3 ,-1 , 0
       0     .12       0  233.93    .045       0     249     .12       0
Bank Sta=233.93,249
XS Rating Curve= 0 ,0
Exp/Cntr=0.3,0.1

Type RM Length L Ch R = 1 ,11469.7 ,227.5,233.6,239.4
XS GIS Cut Line= 3
     2371089.315       419854.83     2370973.213      419654.092
     2370964.532      419552.096
#Sta/Elev= 30
       0  552.91       8  548.94      16  545.44      40  532.92      48  528.54
      64  518.49      72  514.04      76  512.08      92  505.83     104  502.65
     120  499.11   123.9  498.69   131.9  499.84   135.9  499.72   143.3  498.22
   151.9  497.24   155.9  497.51   158.3  498.21   163.9  499.91   199.9  500.73
   203.9  501.26   215.9  504.15   223.9  505.11   235.8  505.86   243.7  507.32
   251.6  509.86   259.5  513.18     287  527.16   322.4  544.15   334.3  548.98
#Mann= 3 ,-1 , 0
       0     .12       0   143.3    .045       0   158.3     .12       0
Bank Sta=143.3,158.3
XS Rating Curve= 0 ,0
Exp/Cntr=0.3,0.1

Type RM Length L Ch R = 1 ,11236.1 ,261.1,286.7,311.9
XS GIS Cut Line= 3
     2371218.438      419801.662     2371234.714      419679.049
     2371192.397      419522.799
#Sta/Elev= 30
       0  534.93      20  526.72    35.9  519.94    47.9   515.4    67.8  508.42
    87.8  502.59    99.8  500.08   119.7  497.64   131.6  496.81   147.4  496.29
   151.3  495.31   155.3  494.02   159.2  493.36   171.1  494.28     179  496.19
   206.6   495.8   210.6  496.01   214.5   497.2   218.4  499.48   222.4  502.31
   230.3  508.55   234.2  511.89   242.1   517.5     250  523.98     254  527.03
   257.9  529.82   261.9  532.33   273.7  540.47   281.6  546.27   285.6  548.98
#Mann= 3 ,-1 , 0
       0     .12       0   155.3    .045       0   171.1     .12       0
Bank Sta=155.3,171.1
XS Rating Curve= 0 ,0
Exp/Cntr=0.3,0.1

Type RM Length L Ch R = 1 ,10949.4 ,292.9,266.5,239.9
XS GIS Cut Line= 3
      2371317.18       419775.62     2371498.386      419599.839
      2371482.11      419475.056
#Sta/Elev= 30
       0   518.5    15.8  515.22    31.6  512.66    51.3  510.64      71  506.73
    82.8  505.28    86.8  503.31    90.7   500.4    94.7  498.26    98.6  497.05
   110.4  494.55   130.2  492.37   138.1  491.07   153.8  491.45   173.6  490.15
  180.21 488.416   189.3     488  194.24 488.402   205.1  491.71   220.9  492.77
   252.5  493.53     280  494.97   299.6  496.77   303.6  497.76   323.2  504.41
   331.1  507.68   350.8  517.89   362.6  524.88   370.4  528.41   378.3  532.96
#Mann= 3 ,-1 , 0
       0     .12       0  180.21    .045       0  194.24     .12       0
#XS Ineff= 2 , 0
          149.85  492.06
Permanent Ineff=
       F       F
Bank Sta=180.21,194.24
XS Rating Curve= 0 ,0
Exp/Cntr=0.3,0.1

Type RM Length L Ch R = 1 ,10682.9 ,207.8,209.6,210.8
XS GIS Cut Line= 3
     2371677.423      419796.236      2371704.55      419709.431
     2371611.234       419463.12
#Sta/Elev= 30
       0  516.23    15.8  513.55    23.7  511.57    35.6  509.39    39.5  508.44
    47.4  505.31    59.3   503.9      83     497      91  494.99  100.03490.8991
   106.9  487.79   114.9  485.93   118.9   484.5   122.9  483.02   126.9  482.81
   130.8  483.43   133.2 484.468   138.8  486.16   142.8  486.56   158.8   486.1
   178.7  487.04   186.7  486.88   222.6  488.48   274.5  489.54   286.5  490.42
   290.5  491.36   298.5  494.25   310.4  500.11   326.4   509.2   354.3  526.45
#Mann= 4 ,-1 , 0
       0     .06       0  100.03     .12       0   118.9    .045       0
   133.2     .12       0
#XS Ineff= 2 , 0
                          192.78          487.94
Permanent Ineff=
       F       F
Bank Sta=118.9,133.2
XS Rating Curve= 0 ,0
Exp/Cntr=0.3,0.1

Type RM Length L Ch R = 1 ,10473.3 ,227,233.9,236.2
XS GIS Cut Line= 3
     2371885.756       419773.45     2371913.968      419693.155
     2371824.992      419404.526
#Sta/Elev= 30
       0  499.35    15.5   495.8    23.2  493.52    34.8  491.66    46.4  487.74
      58  485.89    73.5  485.56     105  484.04   112.9   484.3   128.8  483.78
   152.7  484.15   164.6  483.17   172.5  481.64   184.5  481.15     187481.6308
   192.4  483.19   196.4  483.63   212.3  483.55   224.2     483   232.2  482.15
   244.1  483.85     260  484.63   271.9  484.46   295.7  486.16   319.6   488.5
   327.5  490.12   335.5  491.13   355.4  496.22   371.2  500.83   387.1  504.56
#Mann= 3 ,-1 , 0
       0     .12       0   172.5    .045       0     187     .12       0
#XS Ineff= 2 , 0
                          260.47          485.07
Permanent Ineff=
       F       F
Bank Sta=172.5,187
XS Rating Curve= 0 ,0
Exp/Cntr=0.3,0.1

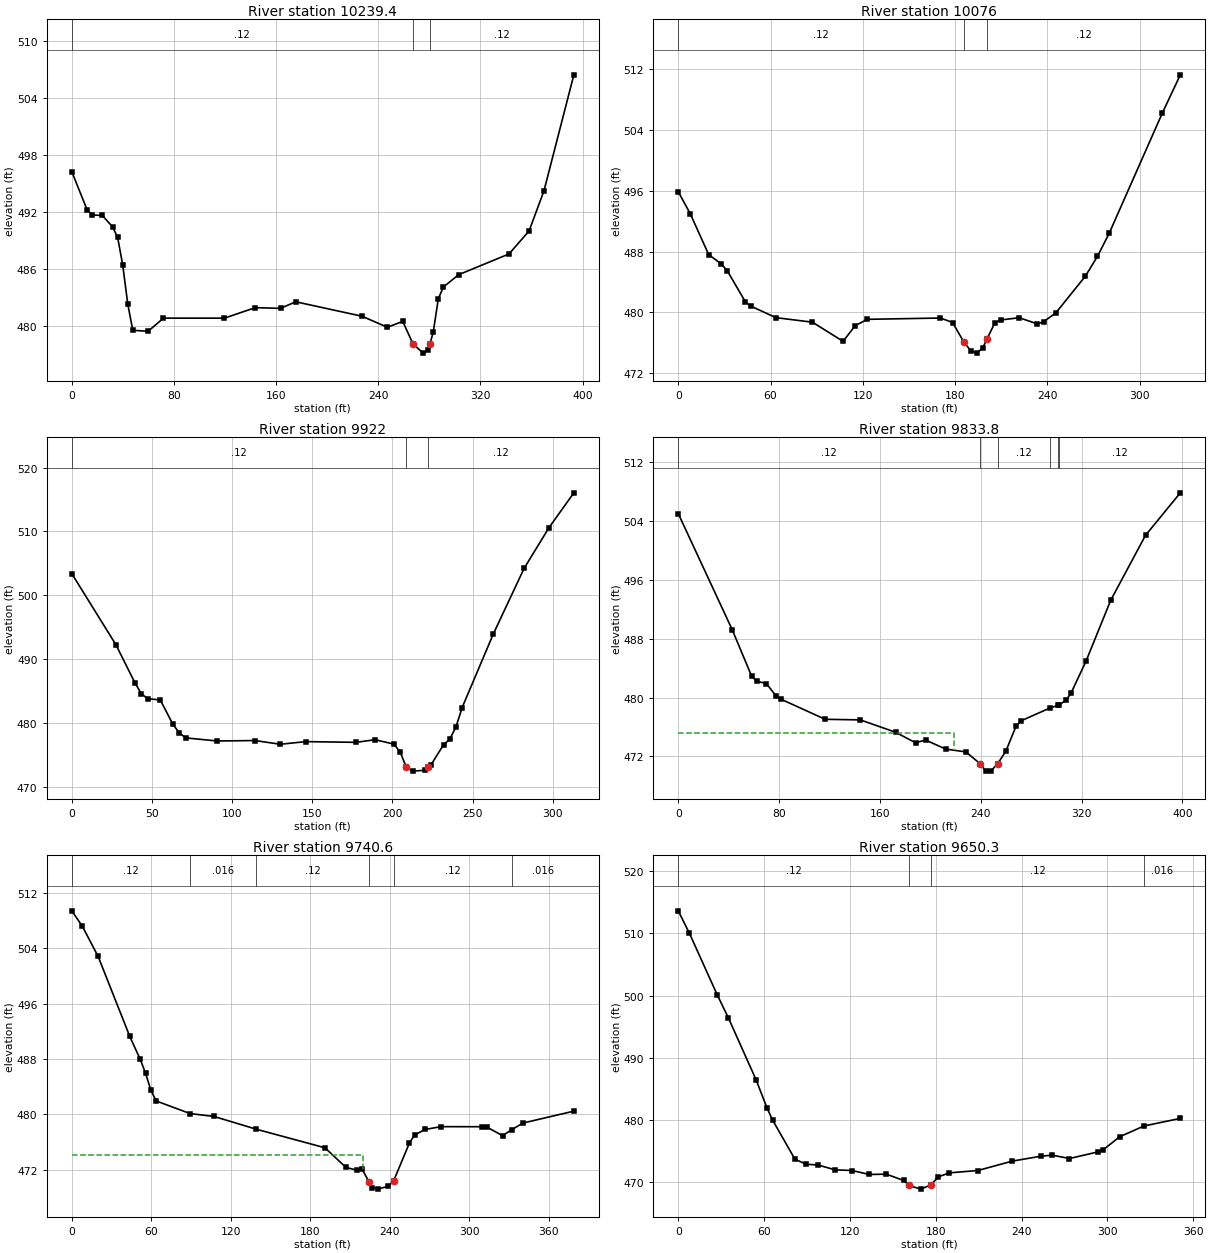
Type RM Length L Ch R = 1 ,10239.4 ,160.7,163.5,165
XS GIS Cut Line= 3
     2372076.077      419747.799     2372018.786      419433.997
     2372020.088      419359.778
#Sta/Elev= 30
       0  496.25      12  492.24      16  491.69    23.9  491.64    31.9  490.45
    35.9  489.34    39.9  486.43    43.9  482.28    47.8  479.56    59.8  479.46
    71.8  480.84   119.6  480.84   143.6  481.94   163.5  481.87   175.4  482.56
   227.3  481.04   247.2  479.88   259.2   480.5   267.2  478.14   275.1  477.16
   279.1  477.44  280.43478.0851   283.1  479.38   287.1   482.9   291.1  484.12
     303  485.41   342.4  487.59   358.1     490   369.8  494.23   393.2  506.43
#Mann= 3 ,-1 , 0
       0     .12       0   267.2    .045       0  280.43     .12       0
Bank Sta=267.2,280.43
XS Rating Curve= 0 ,0
Exp/Cntr=0.3,0.1

Type RM Length L Ch R = 1 ,10076   ,156.2,154,150.8
XS GIS Cut Line= 4
     2372196.086      419717.026     2372159.194      419574.882
     2372148.343      419472.886     2372192.831      419409.952
#Sta/Elev= 30
       0  495.89     7.9  492.95    19.8  487.61    27.8  486.41    31.8  485.51
    43.7  481.38    47.6  480.79    63.5  479.31    87.3  478.71   107.2  476.19
   115.1  478.26     123  479.09   170.5  479.26   178.4  478.67   185.6  476.15
   190.2  474.95   194.2  474.64   198.1  475.35   200.6  476.44     206  478.66
     210  479.01   221.8   479.3   233.6  478.48   237.6  478.78   245.5  479.92
   264.8  484.78   272.6  487.37   280.2  490.39   314.9  506.28   326.5  511.27
#Mann= 3 ,-1 , 0
       0     .12       0   185.6    .045       0   200.6     .12       0
Bank Sta=185.6,200.6
XS Rating Curve= 0 ,0
Exp/Cntr=0.3,0.1

Type RM Length L Ch R = 1 ,9922    ,69.7,88.2,107.6
XS GIS Cut Line= 3
     2372272.041       419702.92     2372305.678      419508.693
     2372278.551      419395.846
#Sta/Elev= 30
       0  503.39    27.6  492.22    39.4  486.28    43.4  484.58    47.3   483.8
    55.2   483.6    63.1  479.78      67  478.47      71  477.66    90.7  477.17
   114.3  477.24   130.1  476.66   145.9  477.07   177.4  476.96   189.2  477.37
     201  476.68   204.9  475.42   208.7  473.06   212.6  472.45   220.3  472.58
   222.4473.0646   224.2  473.48   231.9  476.57   235.8  477.45   239.7   479.4
   243.5  482.39   262.9   493.9   282.2  504.22   297.7  510.59   313.2  516.04
#Mann= 3 ,-1 , 0
       0     .12       0   208.7    .045       0   222.4     .12       0
Bank Sta=208.7,222.4
XS Rating Curve= 0 ,0
Exp/Cntr=0.3,0.1

Type RM Length L Ch R = 1 ,9833.8  ,94.1,93.2,92.5
XS GIS Cut Line= 4
     2372287.232      419712.686     2372316.529      419599.839
      2372417.44      419446.844      2372342.57      419382.825
#Sta/Elev= 30
       0  505.05    42.8  489.26    58.3  482.91    62.2  482.26      70  481.91
    77.7  480.22    81.6  479.79   116.6  477.06   144.5  476.98   172.4   475.3
   188.3  473.87   196.3  474.24   212.2  473.01   228.2  472.63   239.5  471.03
   244.1  470.01   248.1  470.03  253.54471.0311     260  472.74     268   476.1
     272  476.85  295.17478.6153  301.37478.9455   302.3479.0123   307.8  479.68
   311.7  480.63   323.5  484.94   343.2  493.26   370.8  502.09   398.4  507.87
#Mann= 6 ,-1 , 0
       0     .12       0   239.5    .045       0  253.54     .12       0
  295.17    .016       0  301.37     .06       0   302.3     .12       0
#XS Ineff= 2 , 0
           219.2   475.2
Permanent Ineff=
       F       F
Bank Sta=239.5,253.54
XS Rating Curve= 0 ,0
Exp/Cntr=0.3,0.1

Type RM Length L Ch R = 1 ,9740.6  ,96.7,90.2,83.3
XS GIS Cut Line= 4
     2372449.992      419710.516       2372413.1      419609.604
     2372514.011       419456.61     2372538.968      419371.974
#Sta/Elev= 30
       0   509.4       8  507.17    19.9  502.81    43.8  491.26    51.7  487.94
    55.7  485.96    59.7   483.5    63.7  481.95   89.38480.1261   107.4  479.71
  139.37477.8656   191.1  475.19     207  472.35     215  471.97     219  472.16
  224.26470.3137     227  469.43     231  469.22   238.9  469.64   242.9  470.39
   254.9  475.88   258.8  477.04   266.8  477.84   278.8  478.24   309.9  478.23
   313.7  478.14   325.2  476.94  332.34477.8213   340.6  478.76     379  480.48
#Mann= 6 ,-1 , 0
       0     .12       0   89.38    .016       0  139.37     .12       0
  224.26    .045       0   242.9     .12       0  332.34    .016       0
#XS Ineff= 2 , 0
          219.61  474.19
Permanent Ineff=
       F       F
Bank Sta=224.26,242.9
XS Rating Curve= 0 ,0
Exp/Cntr=0.3,0.1

Type RM Length L Ch R = 1 ,9650.3  ,244.6,228.2,211.4
XS GIS Cut Line= 4
     2372545.478      419701.835     2372540.053      419620.455
     2372598.647      419425.142     2372576.945      419363.294
#Sta/Elev= 30
       0  513.65     7.8  510.04    27.2  500.15      35  496.44    54.4  486.45
    62.1  481.88      66  479.93    81.6  473.64    89.6  472.83    97.6  472.72
   109.6  471.94   121.5  471.83   133.5  471.19   145.5  471.24   157.5  470.23
   161.5  469.42   169.5  468.83     177  469.54   181.5  470.77   189.5  471.45
   209.5  471.83   233.5  473.34   253.5  474.13   261.5   474.3   273.5  473.76
   293.2  474.81     297  475.15   308.6  477.26  325.54478.9964     351  480.22
#Mann= 4 ,-1 , 0
       0     .12       0   161.5    .045       0     177     .12       0
  325.54    .016       0
Bank Sta=161.5,177
XS Rating Curve= 0 ,0
Exp/Cntr=0.3,0.1

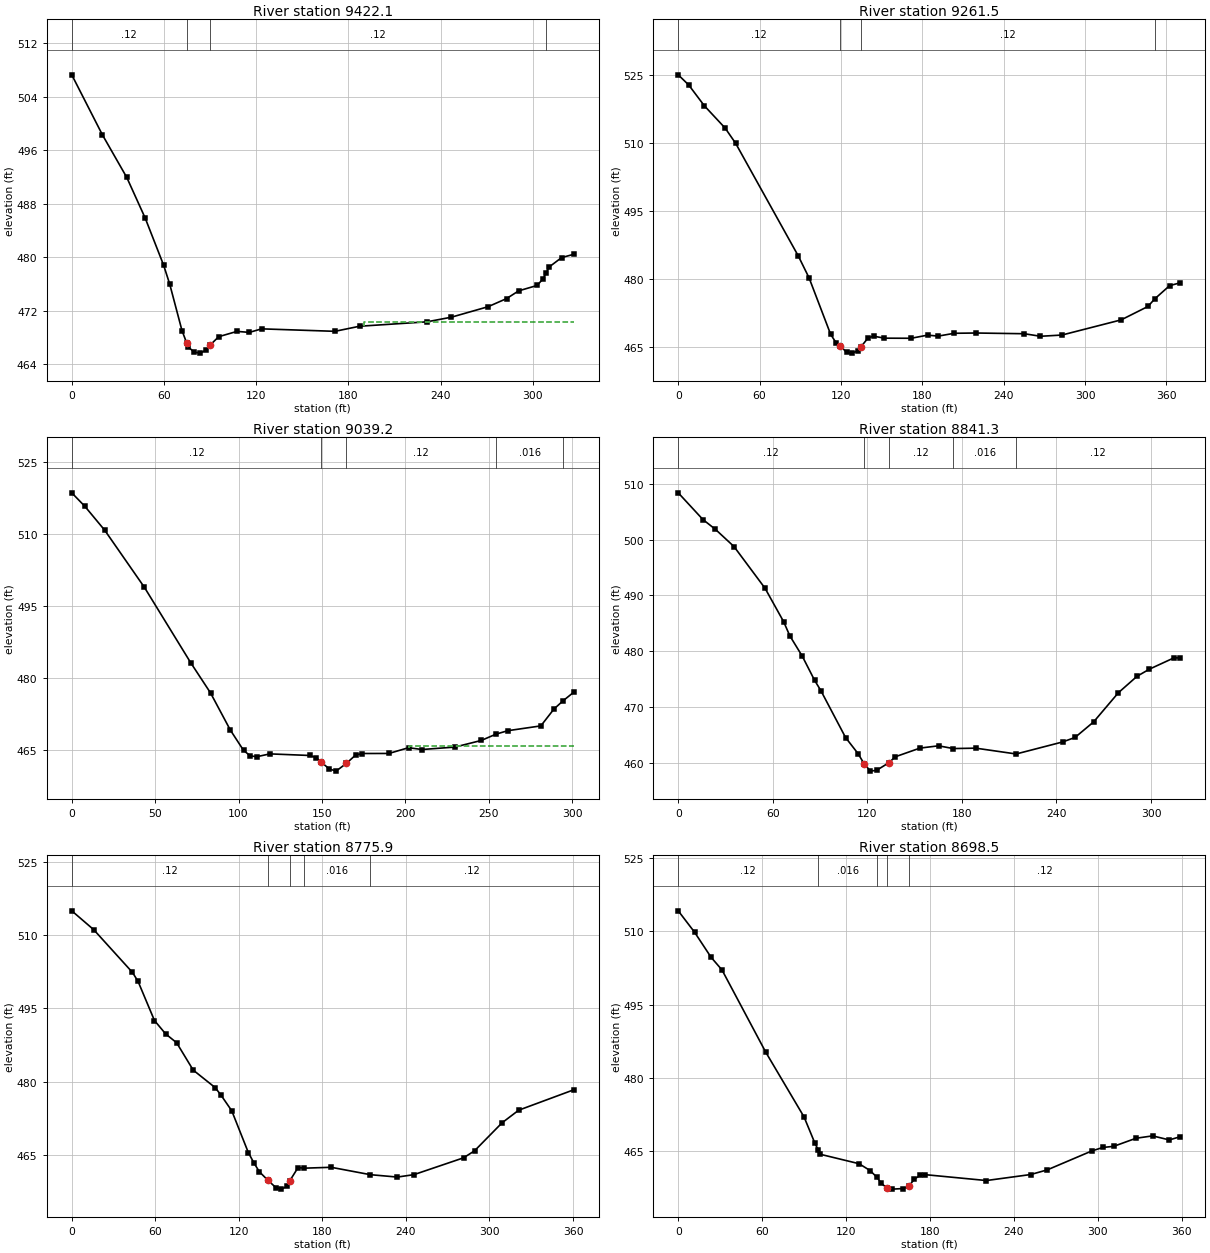
Type RM Length L Ch R = 1 ,9422.1  ,163.7,160.6,157.1
XS GIS Cut Line= 2
     2372807.848      419621.497      2372677.64      419322.017
#Sta/Elev= 30
       0  507.25    19.9  498.29    35.8   491.9    47.8  485.81    59.7  478.82
    63.7  475.97    71.7  469.01    74.8  467.13    75.7  466.58    79.6  465.79
    83.6  465.64    87.6  466.13    89.8   466.8    95.6   468.1   107.5  468.89
   115.5  468.74   123.5  469.27   171.2   468.9   187.2  469.66     231  470.32
   246.9  471.01   270.8  472.58   282.8  473.79   290.7  474.95   302.7  475.76
   306.6  476.76  308.71477.6937   310.6  478.53   318.6  479.92   326.6  480.42
#Mann= 4 ,-1 , 0
       0     .12       0    74.8    .045       0    89.8     .12       0
  308.71    .016       0
#XS Ineff= 2 , 0
                          190.35           470.3
Permanent Ineff=
       F       F
Bank Sta=74.8,89.8
XS Rating Curve= 0 ,0
Exp/Cntr=0.3,0.1

Type RM Length L Ch R = 1 ,9261.5  ,227.3,222.3,217.1
XS GIS Cut Line= 3
     2373013.143        419544.5     2372935.802      419510.258
     2372783.109      419268.892
#Sta/Elev= 30
       0  524.98     7.7  522.75    19.2  518.17    34.6  513.22    42.3  509.88
    88.6  484.96    96.5  480.15   112.4  467.69   116.3  465.89   119.4  465.18
   124.2  463.72   128.2  463.56   132.2  464.05   134.4  464.83   140.1  466.96
   144.1   467.3     152  466.86   171.8  466.84   183.8  467.53   191.7  467.32
   203.6  467.94   219.4     468   255.2  467.84   267.1  467.28   282.9  467.55
   326.6   470.9   346.4  473.87   351.2 475.491   362.3  478.45   370.2  479.09
#Mann= 4 ,-1 , 0
       0     .12       0   119.4    .045       0   134.4     .12       0
   351.2    .016       0
Bank Sta=119.4,134.4
XS Rating Curve= 0 ,0
Exp/Cntr=0.3,0.1

Type RM Length L Ch R = 1 ,9039.2  ,194.8,197.9,198.3
XS GIS Cut Line= 2
     2373122.952       419398.84     2372910.713      419185.299
#Sta/Elev= 30
       0   518.6     7.9  515.77    19.8  510.79    43.6   498.9    71.3  483.24
    83.2  476.94    95.1   469.2     103  464.98     107  463.84   110.9  463.65
   118.8  464.24   142.6  463.91   146.6  463.46   149.6  462.51   154.5   461.1
   158.5  460.65   164.6  462.24   170.3  464.02   174.3  464.32   190.2  464.33
     202  465.53     210  465.15   229.8  465.66   245.6  467.04  254.45468.3559
   261.5  469.07   281.3  470.07   289.2  473.59  294.75475.3294   301.1   477.1
#Mann= 5 ,-1 , 0
       0     .12       0   149.6    .045       0   164.6     .12       0
  254.45    .016       0  294.75     .12       0
#XS Ineff= 2 , 0
                          202.27          465.98
Permanent Ineff=
       F       F
Bank Sta=149.6,164.6
XS Rating Curve= 0 ,0
Exp/Cntr=0.3,0.1

Type RM Length L Ch R = 1 ,8841.3  ,72.4,65.4,60.1
XS GIS Cut Line= 3
     2373186.754      419324.231     2373179.159      419222.235
     2373026.164       419069.24
#Sta/Elev= 30
       0   508.4    15.7   503.6    23.6  501.85    35.4  498.76    55.1  491.28
    66.9  485.28    70.8  482.76    78.7  479.11    86.5  474.79    90.5  472.93
   106.2  464.51   114.1  461.63     118  459.79     122  458.49   125.9  458.64
   133.8  460.02   137.7  461.06   153.4  462.62   165.2  463.03  174.53 462.536
   188.8  462.61  214.43461.5663   243.9  463.72   251.8  464.53   263.6  467.32
   279.3  472.55   291.1  475.49     299  476.78   314.7  478.82   318.6  478.78
#Mann= 5 ,-1 , 0
       0     .12       0     118    .045       0   133.8     .12       0
  174.53    .016       0  214.43     .12       0
Bank Sta=118,133.8
XS Rating Curve= 0 ,0
Exp/Cntr=0.3,0.1

Type RM Length L Ch R = 1 ,8775.9  ,77.2,77.4,77.9
XS GIS Cut Line= 2
     2373339.749      419239.596     2373030.504      419054.049
#Sta/Elev= 30
       0  514.94    15.8  511.07    43.6  502.33    47.6   500.5    59.4  492.48
    67.4  489.75    75.3  487.94    87.2  482.34     103  478.75     107  477.28
   114.9  474.01   126.8  465.46   130.8  463.35   134.7  461.54   140.9 459.772
   146.6  458.28   150.6  457.97   154.6  458.54  156.43459.6085   162.5  462.37
  167.07462.2599   186.3  462.44  214.51460.9249   233.8  460.44   245.7  460.93
   281.4  464.38   289.3  465.82   309.1  471.56     321  474.13   360.6  478.31
#Mann= 5 ,-1 , 0
       0     .12       0   140.9    .045       0  156.43     .12       0
  167.07    .016       0  214.51     .12       0
Bank Sta=140.9,156.43
XS Rating Curve= 0 ,0
Exp/Cntr=0.3,0.1

Type RM Length L Ch R = 1 ,8698.5  ,143.9,149,153.4
XS GIS Cut Line= 3
      2373352.77      419209.214     2373284.538      419118.578
     2373073.907        418992.2
#Sta/Elev= 30
       0   514.2    11.7  509.81    23.5  504.68    31.3  502.09    62.6  485.24
      90  471.97    97.8  466.56  100.31465.1184   101.7  464.32   129.3   462.4
   137.2     461  142.25459.5773   145.1  458.43   149.1  457.44   153.1  457.19
     161  457.31     165  457.82   168.9  459.24   172.9  459.99   176.8  460.15
   220.4  458.95   252.1  460.18     264  461.14   295.7     465   303.6  465.72
   311.5  465.96   327.4  467.61   339.3   468.1   351.2  467.27   359.1  467.93
#Mann= 5 ,-1 , 0
       0     .12       0  100.31    .016       0  142.25     .12       0
   149.1    .045       0     165     .12       0
Bank Sta=149.1,165
XS Rating Curve= 0 ,0
Exp/Cntr=0.3,0.1

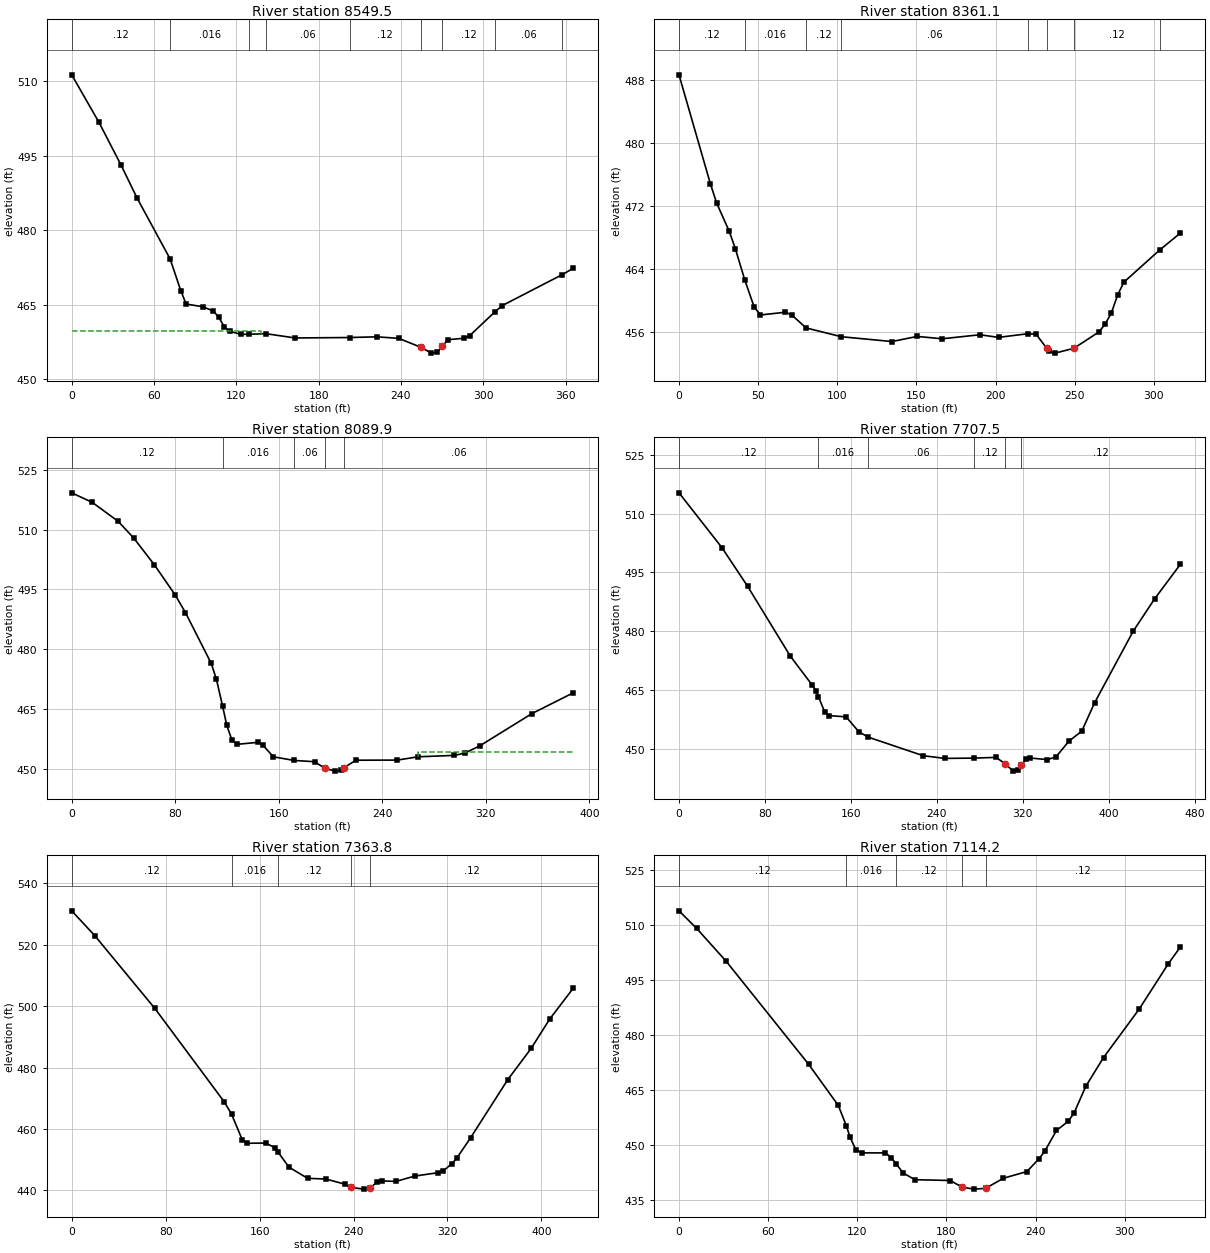
Type RM Length L Ch R = 1 ,8549.5  ,187.3,188.4,188.6
XS GIS Cut Line= 2
     2373438.491      419128.919     2373169.393      418881.523
#Sta/Elev= 30
       0  511.24    19.9  501.66    35.8  493.17    47.7  486.42   71.69474.2242
    79.5  467.83    83.4  465.13    95.4   464.6   103.3  463.72   107.3  462.43
   111.2  460.57   115.2  459.65   123.2  459.05  129.51459.0542  141.53459.1726
   162.9  458.31   202.6   458.4   222.5  458.54   238.4  458.23   254.3  456.46
   262.2  455.26   266.2   455.4   270.2  456.64   274.2  457.96   286.1  458.26
     290  458.74  308.34463.5249   313.9  464.83  357.49471.0365   365.5   472.3
#Mann= 9 ,-1 , 0
       0     .12       0   71.69    .016       0  129.51     .12       0
  141.53     .06       0   202.6     .12       0   254.3    .045       0
   270.2     .12       0  308.34     .06       0  357.49    .016       0
#XS Ineff= 2 , 0
          138.29  459.81
Permanent Ineff=
       F       F
Bank Sta=254.3,270.2
XS Rating Curve= 0 ,0
Exp/Cntr=0.3,0.1

Type RM Length L Ch R = 1 ,8361.1  ,262.6,271.2,274.3
XS GIS Cut Line= 2
     2373537.015      418978.267      2373309.15      418758.215
#Sta/Elev= 30
       0  488.62    19.8  474.82    23.8  472.35    31.7  468.79    35.6  466.57
   41.54462.6166    47.5  459.16    51.5  458.15    67.3   458.5    71.3  458.14
   80.37456.5039  102.68 455.388   134.6  454.78   150.5  455.43   166.3  455.13
   190.1  455.64   201.9  455.31  220.58455.7743   225.7   455.7  232.42453.9064
   233.6  453.52   237.6  453.31   249.5  453.92   265.3  455.99   269.3     457
   273.2  458.41   277.2   460.7   281.1  462.31  303.82466.4083   316.8  468.54
#Mann= 8 ,-1 , 0
       0     .12       0   41.54    .016       0   80.37     .12       0
  102.68     .06       0  220.58     .12       0  232.42    .045       0
   249.5     .12       0  303.82     .06       0
Bank Sta=232.42,249.5
XS Rating Curve= 0 ,0
Exp/Cntr=0.3,0.1

Type RM Length L Ch R = 1 ,8089.9  ,383.8,382.4,382.8
XS GIS Cut Line= 2
     2373719.306      418886.514     2373476.251      418584.865
#Sta/Elev= 30
       0  519.19      16  516.77    35.9  512.05    47.9  507.88    63.9  501.16
    79.9  493.65    87.9  489.21   107.8   476.5   111.8  472.52  116.58  465.82
   119.8  460.99   123.8  457.32   127.8  456.26   143.8  456.75   147.8  456.02
   155.8  453.13  171.97  452.22   187.7  451.91   195.5  450.27   203.7  449.55
   207.7  449.72   210.5  450.43   219.6  452.28   251.6  452.31   267.6  453.14
   295.5  453.48   303.5  454.03   315.5  455.91   355.4  463.91   387.4  469.13
#Mann= 5 ,-1 , 0
       0     .12       0  116.58    .016       0  171.97     .06       0
   195.5    .045       0   210.5     .06       0
#XS Ineff= 2 , 0
                          267.91          454.32
Permanent Ineff=
       F       F
Bank Sta=195.5,210.5
XS Rating Curve= 0 ,0
Exp/Cntr=0.3,0.1

Type RM Length L Ch R = 1 ,7707.5  ,328,343.7,358.9
XS GIS Cut Line= 2
     2373974.515      418712.252     2373717.353      418322.712
#Sta/Elev= 30
       0   515.3    39.9  501.34    63.8  491.48   103.7  473.59   123.7  466.34
   127.7  464.75  129.85463.2505   135.6  459.42   139.6  458.44   155.6  458.11
   167.6  454.27   176.4452.9145   227.4   448.2   247.4  447.51  275.09447.5858
   295.2  447.77   303.6  446.15   311.2  444.26   315.2   444.6   318.6   445.7
   323.2  447.31   327.1  447.61   343.1  447.19   351.1  447.92     363   451.9
     375  454.46     387  461.73   422.9  479.98   442.8  488.22   466.8  497.04
#Mann= 6 ,-1 , 0
       0     .12       0  129.85    .016       0   176.4     .06       0
  275.09     .12       0   303.6    .045       0   318.6     .12       0
Bank Sta=303.6,318.6
XS Rating Curve= 0 ,0
Exp/Cntr=0.3,0.1

Type RM Length L Ch R = 1 ,7363.8  ,257.6,249.5,240.6
XS GIS Cut Line= 3
     2374151.381      418585.299     2374081.937       418444.24
     2374112.319      418176.228
#Sta/Elev= 30
       0  531.05    19.6  522.97    70.8  499.24   129.7  468.91  136.08464.8266
   145.4   456.3   149.4   455.3   165.2   455.4   173.1  453.84  175.66452.4704
     185  447.53   200.9  443.89   216.7  443.65   232.6  441.98   237.5  440.96
   248.5  440.37  254.34440.9001   260.4  442.71   264.3  443.04   276.2  442.89
   292.1  444.62   311.9  445.72   315.9  446.18   323.8  448.66   327.8  450.38
   339.7   457.1   371.4  476.06   391.3  486.23   407.1  495.79     427  505.76
#Mann= 5 ,-1 , 0
       0     .12       0  136.08    .016       0  175.66     .12       0
   237.5    .045       0  254.34     .12       0
Bank Sta=237.5,254.34
XS Rating Curve= 0 ,0
Exp/Cntr=0.3,0.1

Type RM Length L Ch R = 1 ,7114.2  ,262.6,256.1,250
XS GIS Cut Line= 2
     2374374.905      418482.217      2374285.93      418156.696
#Sta/Elev= 30
       0  513.94    11.9  509.15    31.8  500.17    87.3   472.1   107.2  460.92
   112.6 455.419   115.1  452.31   119.1  448.76   123.1  447.97     139  447.96
   142.9  446.67  146.38444.8865   150.9   442.5   158.8  440.66   182.6  440.44
   190.6  438.62   198.5  438.09   206.4   438.3   218.4  441.06   234.2  442.88
   242.2   446.3   246.2  448.38   254.1  454.08     262  456.56     266  458.88
   273.9  466.15   285.8  473.96   309.7   487.1   329.5  499.58   337.5  504.08
#Mann= 5 ,-1 , 0
       0     .12       0   112.6    .016       0  146.38     .12       0
   190.6    .045       0   206.4     .12       0
Bank Sta=190.6,206.4
XS Rating Curve= 0 ,0
Exp/Cntr=0.3,0.1