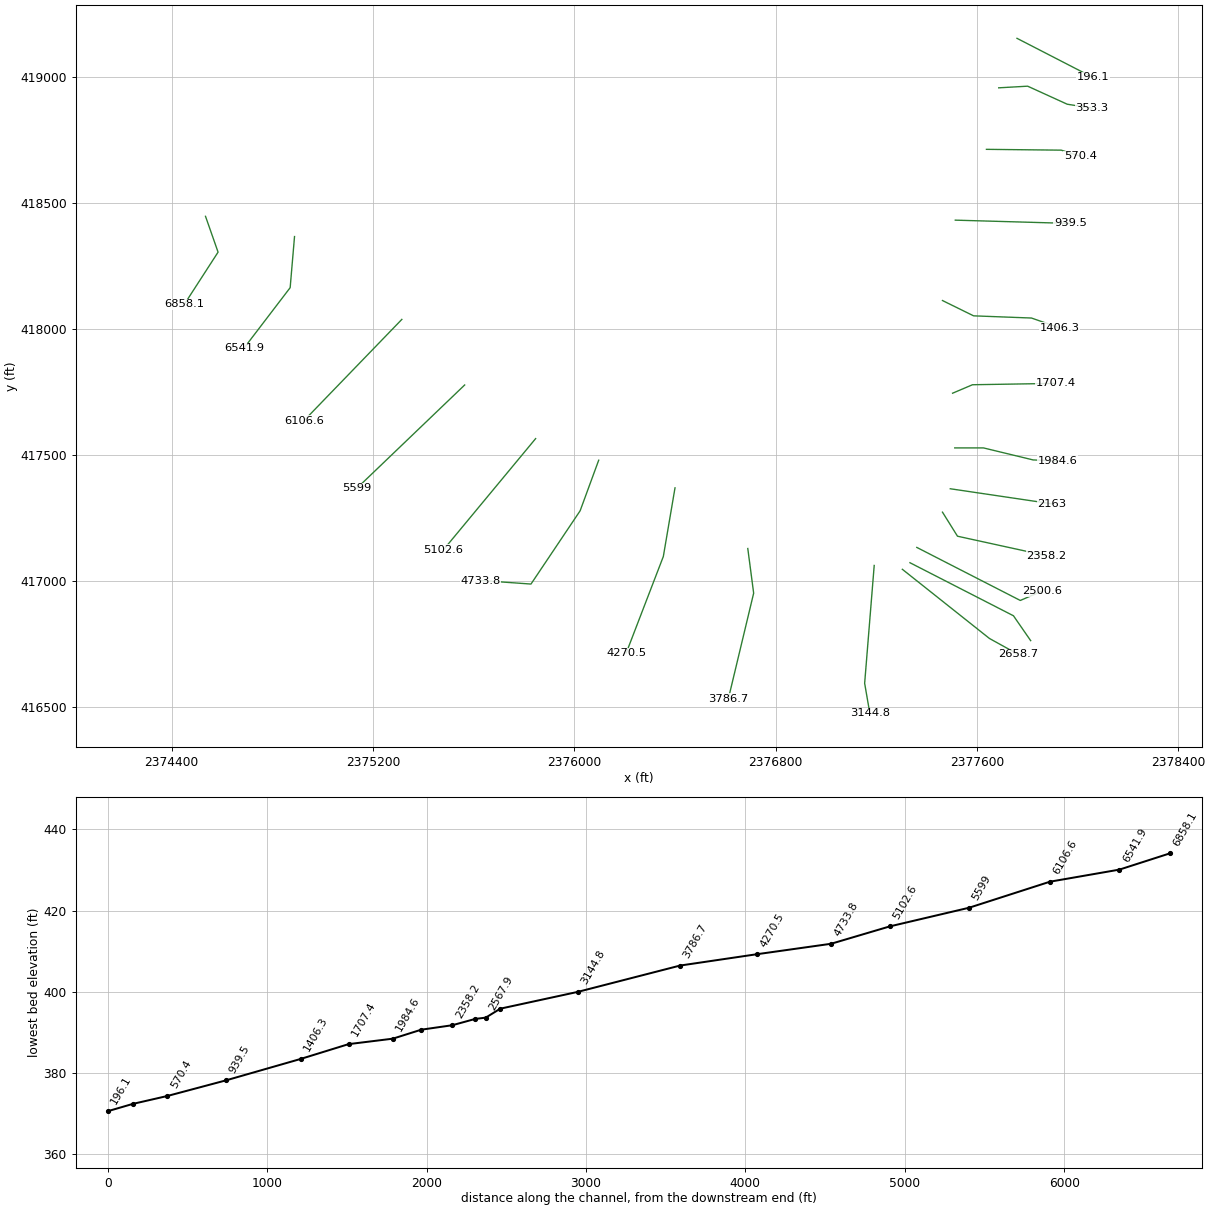
HEC-RAS study BIGRUN2.prj: BIGRUN2

--- BIGRUN2.g01 (geometry) --- (continued)

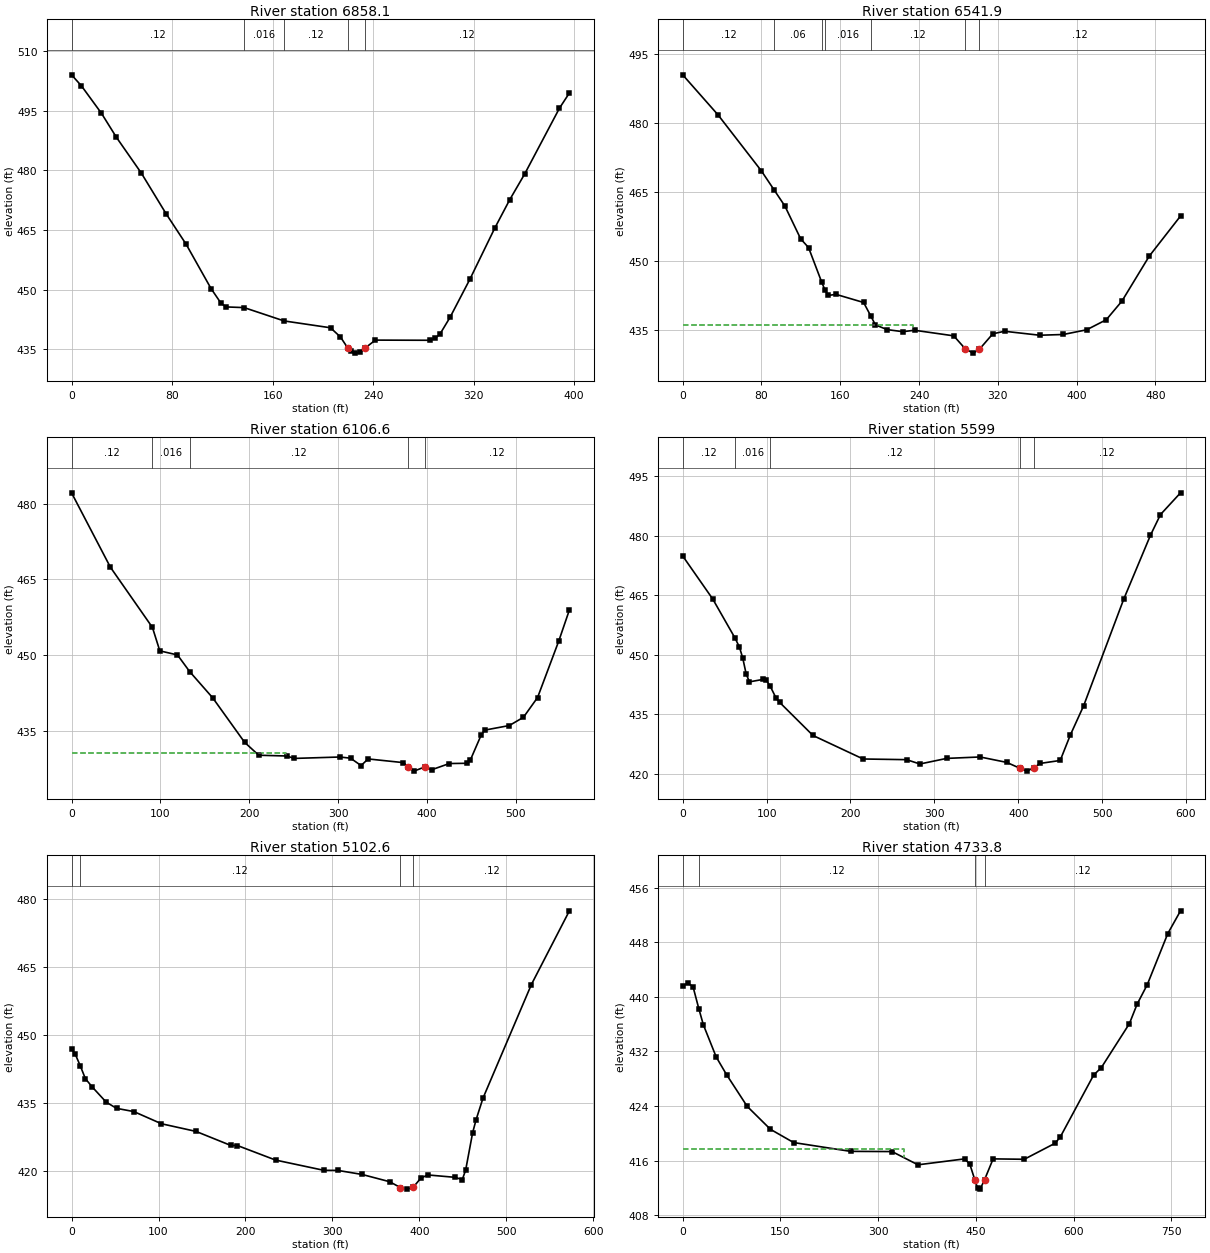
Type RM Length L Ch R = 1 ,6858.1  ,318.6,316.2,313.5
XS GIS Cut Line= 3
     2374534.411      418447.495     2374584.324      418305.351
      2374450.86      418099.188
#Sta/Elev= 30
       0     504     7.9  501.21    23.8  494.33    35.7   488.3    55.5  479.32
    75.3  469.06    91.2  461.42     111   450.3   118.9  446.63   122.9  445.68
  137.35445.5097  169.09442.1628   206.1  440.44     214  438.12  219.63435.4427
     222   434.6   225.9  434.07   229.9  434.32   233.8  435.39   241.8  437.34
   285.3   437.3   289.3  437.76   293.3  438.91   301.2  443.05     317  452.63
   336.8  465.48   348.7  472.61   360.6  479.08   388.3  495.62   396.2  499.44
#Mann= 5 ,-1 , 0
       0     .12       0  137.35    .016       0  169.09     .12       0
  219.63    .045       0   233.8     .12       0
Bank Sta=219.63,233.8
XS Rating Curve= 0 ,0
Exp/Cntr=0.3,0.1

Type RM Length L Ch R = 1 ,6541.9  ,440.1,435.3,429.3
XS GIS Cut Line= 3
     2374888.143        418367.2     2374870.782      418164.292
     2374687.405      417924.491
#Sta/Elev= 30
       0  490.43    35.9  481.74    79.9   469.6   93.14465.3744   103.8  461.97
   119.8  454.86   127.8  452.97  141.01445.5515  144.36443.8112   147.8  442.59
   155.7  442.82   183.7  441.06  190.95438.1544   195.7   436.2   207.6  435.18
   223.5  434.73   235.4  435.04   275.2  433.83   287.1  430.97     295  430.08
   301.1  430.87   314.9  434.27   326.8  434.82   362.5  433.96   386.4  434.12
   410.2  435.14   430.1  437.32     446  441.36   473.8  451.13   505.5  459.81
#Mann= 7 ,-1 , 0
       0     .12       0   93.14     .06       0  141.01     .12       0
  144.36    .016       0  190.95     .12       0   287.1    .045       0
   301.1     .12       0
#XS Ineff= 2 , 0
          234.06  436.15
Permanent Ineff=
       F       F
Bank Sta=287.1,301.1
XS Rating Curve= 0 ,0
Exp/Cntr=0.3,0.1

Type RM Length L Ch R = 1 ,6106.6  ,521.2,507.6,526.4
XS GIS Cut Line= 2
     2375314.576      418038.424     2374925.036      417635.863
#Sta/Elev= 30
       0  482.11    43.7  467.41   91.02455.5016    99.3  450.88   119.2  450.07
  132.85446.7938   158.9  441.58   194.7  432.81   210.6  430.25   242.4   430.1
   250.3  429.62   301.9   429.9   313.9  429.67   325.8  428.21   333.7  429.52
   373.4  428.79  378.79427.9633   385.4  427.11   397.3  427.93   405.2  427.38
   425.1  428.61     445  428.66   448.9  429.36   460.8  434.19   464.8  435.21
   492.6  436.12   508.5  437.75   524.4  441.66   548.3  452.85   560.2  458.96
#Mann= 5 ,-1 , 0
       0     .12       0   91.02    .016       0  132.85     .12       0
  378.79    .045       0   397.3     .12       0
#XS Ineff= 2 , 0
          241.49  430.64
Permanent Ineff=
       F       F
Bank Sta=378.79,397.3
XS Rating Curve= 0 ,0
Exp/Cntr=0.3,0.1

Type RM Length L Ch R = 1 ,5599    ,478.3,496.4,497.2
XS GIS Cut Line= 2
     2375564.265      417778.145     2375135.539      417367.851
#Sta/Elev= 30
       0  474.95    35.8   464.1   62.52454.1961    67.7  451.94    71.7  449.11
    75.7  445.15    79.6  443.21    95.6  443.82    99.6  443.61  104.27442.1256
   111.5  439.04   115.5  438.05   155.3  429.69   215.1  423.76   266.8  423.59
   282.8   422.5   314.6  423.91   354.5  424.27   386.3   422.9   402.2   421.4
   410.2   420.7   418.2  421.51   426.2  422.65     450  423.39     462  429.78
   477.9  437.17   525.7  464.06   557.6  480.19   569.5  485.39   593.4  490.87
#Mann= 5 ,-1 , 0
       0     .12       0   62.52    .016       0  104.27     .12       0
   402.2    .045       0   418.2     .12       0
Bank Sta=402.2,418.2
XS Rating Curve= 0 ,0
Exp/Cntr=0.3,0.1

Type RM Length L Ch R = 1 ,5102.6  ,367.6,368.7,368.8
XS GIS Cut Line= 2
      2375846.26      417565.333     2375480.591      417124.795
#Sta/Elev= 30
       0  446.86       4   445.9   10.14443.1716    15.9   440.4    23.9  438.55
    39.8  435.25    51.7  433.88    71.6  433.17   103.4  430.49   143.1  428.81
   182.9  425.74   190.8   425.7   234.6  422.51   290.2  420.25   306.1  420.24
     334  419.35   365.8  417.75   378.1  416.47   385.7  416.12   393.1  416.58
   401.6  418.52   409.5  419.24   441.3  418.71   449.3   418.2   453.2   420.3
   461.2  428.49   465.2  431.38   473.1   436.1   528.8   461.1   572.5   477.3
#Mann= 4 ,-1 , 0
       0    .016       0   10.14     .12       0   378.1    .045       0
   393.1     .12       0
Bank Sta=378.1,393.1
XS Rating Curve= 0 ,0
Exp/Cntr=0.3,0.1

Type RM Length L Ch R = 1 ,4733.8  ,457.4,463.4,469.1
XS GIS Cut Line= 4
     2376096.911      417479.613     2376023.126      417278.875
     2375827.813      416988.077     2375628.161      417002.182
#Sta/Elev= 30
       0  441.58     7.9     442    15.8   441.5   24.75438.2646    31.7  435.91
    51.5  431.18    67.3  428.61      99  423.96   134.7   420.6   170.3  418.66
   257.7  417.37   321.4  417.34   361.2   415.4   432.8  416.27   440.8   415.5
   448.4  413.23   452.7  411.99   456.7  411.84   463.4  413.21   476.6  416.27
   524.4  416.21     572  418.57   579.9  419.51   630.9  428.54   642.7  429.63
   685.8  436.07   697.6  438.91   713.3  441.79   744.7  449.25   764.3  452.59
#Mann= 4 ,-1 , 0
       0    .016       0   24.75     .12       0   448.4    .045       0
   463.4     .12       0
#XS Ineff= 2 , 0
          340.14  417.69
Permanent Ineff=
       F       F
Bank Sta=448.4,463.4
XS Rating Curve= 0 ,0
Exp/Cntr=0.3,0.1

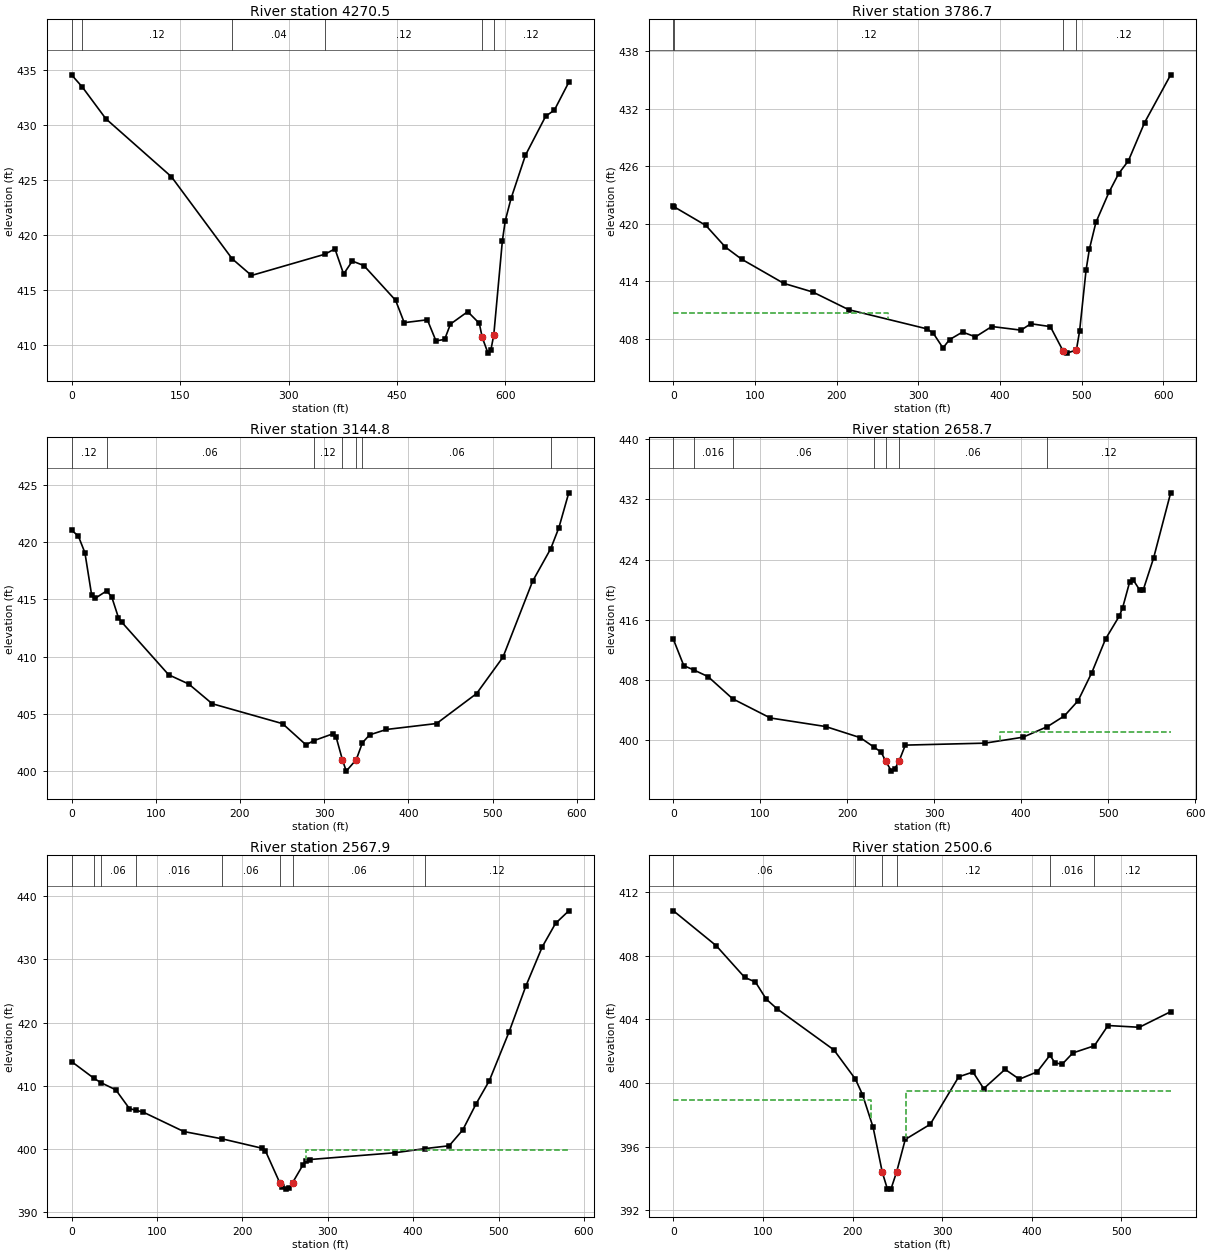
Type RM Length L Ch R = 1 ,4270.5  ,478.4,483.8,481.2
XS GIS Cut Line= 3
     2376400.156      417369.854     2376353.704      417097.339
     2376205.992      416713.721
#Sta/Elev= 30
       0  434.58   14.88433.4751    47.4  430.59   138.2  425.31  222.05417.8594
   248.8  416.34  350.39418.2732   364.2  418.76   376.2  416.47   388.2  417.65
   404.2  417.24   448.1  414.08     460  412.05     492  412.31   503.9  410.39
   515.9  410.53   523.9  411.92   547.8  413.05   563.8  411.99   567.8  410.72
   575.8  409.28   579.8  409.56   583.8  410.92   595.7  419.49   599.7  421.32
   607.7  423.34   627.6  427.27   655.6  430.82   667.6  431.37   687.5   433.9
#Mann= 6 ,-1 , 0
       0    .016       0   14.88     .12       0  222.05     .04       0
  350.39     .12       0   567.8    .045       0   583.8     .12       0
Bank Sta=567.8,583.8
XS Rating Curve= 0 ,0
Exp/Cntr=0.3,0.1

Type RM Length L Ch R = 1 ,3786.7  ,639.4,642,644
XS GIS Cut Line= 3
     2376689.359      417129.136     2376712.684       416951.88
     2376612.319      416533.432
#Sta/Elev= 30
       0  421.81     .65421.7726    39.7  419.82    63.6  417.56    83.4   416.3
   135.1  413.77   170.8  412.86   214.6  411.02   310.3  409.02   318.2  408.57
   330.2  407.02   338.2  407.89   354.1  408.68     370  408.18     390  409.26
   425.8  408.88   437.8  409.55   461.7  409.25   477.6  406.66   481.6  406.48
   493.6   406.8   497.5  408.76   505.5  415.18   509.5  417.33   517.5  420.13
   533.4  423.26   545.4  425.23   557.3  426.57   577.2  430.57   609.1  435.55
#Mann= 4 ,-1 , 0
       0     .06       0     .65     .12       0   477.6    .045       0
   493.6     .12       0
#XS Ineff= 2 , 0
          262.23  410.62
Permanent Ineff=
       F       F
Bank Sta=477.6,493.6
XS Rating Curve= 0 ,0
Exp/Cntr=0.3,0.1

Type RM Length L Ch R = 1 ,3144.8  ,451.1,486,510.7
XS GIS Cut Line= 3
     2377191.746      417061.861     2377153.768      416594.196
     2377174.385      416474.839
#Sta/Elev= 30
       0  421.05       8  420.56    15.9  419.08    23.9  415.38    27.8  415.09
   41.67415.7496    47.7  415.23    55.7  413.41    59.6  413.02   115.3  408.42
   139.2  407.61     167  405.89   250.5  404.15   278.3   402.3  287.52 402.658
   310.2  403.26   314.1  402.98  321.53401.0081   326.1     400     338     401
  345.33402.4807   353.9  403.17   373.8  403.64   433.4  404.16   480.9  406.78
   512.2  409.96   547.4   416.6  568.88419.4357   578.6  421.28   590.3  424.32
#Mann= 7 ,-1 , 0
       0     .12       0   41.67     .06       0  287.52     .12       0
  321.53    .045       0     338     .12       0  345.33     .06       0
  568.88     .12       0
Bank Sta=321.53,338
XS Rating Curve= 0 ,0
Exp/Cntr=0.3,0.1

Type RM Length L Ch R = 1 ,2658.7  ,85.6,90.9,95.4
XS GIS Cut Line= 3
     2377303.508       417046.67     2377649.645      416772.148
     2377763.577      416709.214
#Sta/Elev= 30
       0  413.38    11.9   409.9   23.85409.3012    39.8  408.44   68.11405.4916
   111.4  402.94   175.1   401.8   214.9  400.32   231.2 399.023   238.8   398.4
  244.39397.1555   250.7  395.87   254.7  396.19  259.56 397.222   266.7  399.33
   358.2  399.59     402  400.38   430.1401.7833   449.7  403.22   465.4  405.23
   481.2  408.97     497  413.44   512.8  416.49   516.7  417.62   524.6  420.97
   528.6  421.34   536.4  419.93   540.4  419.99   552.2  424.19   571.9  432.88
#Mann= 7 ,-1 , 0
       0     .12       0   23.85    .016       0   68.11     .06       0
   231.2     .12       0  244.39    .045       0  259.56     .06       0
   430.1     .12       0
#XS Ineff= 2 , 0
                          375.23          401.08
Permanent Ineff=
       F       F
Bank Sta=244.39,259.56
XS Rating Curve= 0 ,0
Exp/Cntr=0.3,0.1

Type RM Length L Ch R = 1 ,2567.9  ,67.4,67.2,67
XS GIS Cut Line= 3
      2377333.89      417072.712     2377745.131      416862.208
     2377813.491      416763.467
#Sta/Elev= 30
       0  413.85   26.18411.2062   34.14 410.532    51.8  409.38    67.7  406.42
   75.17406.1447    83.6  405.87   131.4  402.78  176.13401.6274     223  400.14
     227  399.72   243.8  394.67   246.9  394.02   250.9  393.67   254.9  393.82
   258.8   394.7   270.8  397.47   274.8  398.14   278.8  398.35   378.4  399.42
  413.92400.0823   442.1  400.53     458  403.03   473.6  407.16   489.1  410.82
   512.4   418.6   531.7  425.73   551.1     432   566.6   435.7   582.1  437.69
#Mann= 8 ,-1 , 0
       0     .06       0   26.18     .08       0   34.14     .06       0
   75.17    .016       0  176.13     .06       0   243.8    .045       0
   258.8     .06       0  413.92     .12       0
#XS Ineff= 2 , 0
                           274.3           399.8
Permanent Ineff=
       F       F
Bank Sta=243.8,258.8
XS Rating Curve= 0 ,0
Exp/Cntr=0.3,0.1

Type RM Length L Ch R = 1 ,2500.6  ,136.9,142.4,149
XS GIS Cut Line= 3
     2377361.017      417133.476     2377772.258      416922.972
     2377857.978      416959.865
#Sta/Elev= 30
       0  410.81    47.8  408.62    79.6  406.63    91.6  406.34   103.6  405.27
   115.5  404.67   179.2  402.08  203.21400.2468   211.1  399.28     223  397.22
  233.28394.3915     239  393.34   242.9  393.34  249.31394.4284   258.9  396.46
   286.8  397.41   318.6  400.39   334.5  400.69   346.5  399.65   370.4  400.86
   386.3  400.24   406.2   400.7  420.45401.7425   426.1  401.27   434.1  401.18
   446.1  401.89  470.06402.3385   485.3  403.61   520.3   403.5   555.3  404.48
#Mann= 6 ,-1 , 0
       0     .06       0  203.21     .12       0  233.28    .045       0
  249.31     .12       0  420.45    .016       0  470.06     .12       0
#XS Ineff= 2 , 0
          220.43  398.96  259.44          399.47
Permanent Ineff=
       F       F
Bank Sta=233.28,249.31
XS Rating Curve= 0 ,0
Exp/Cntr=0.3,0.1

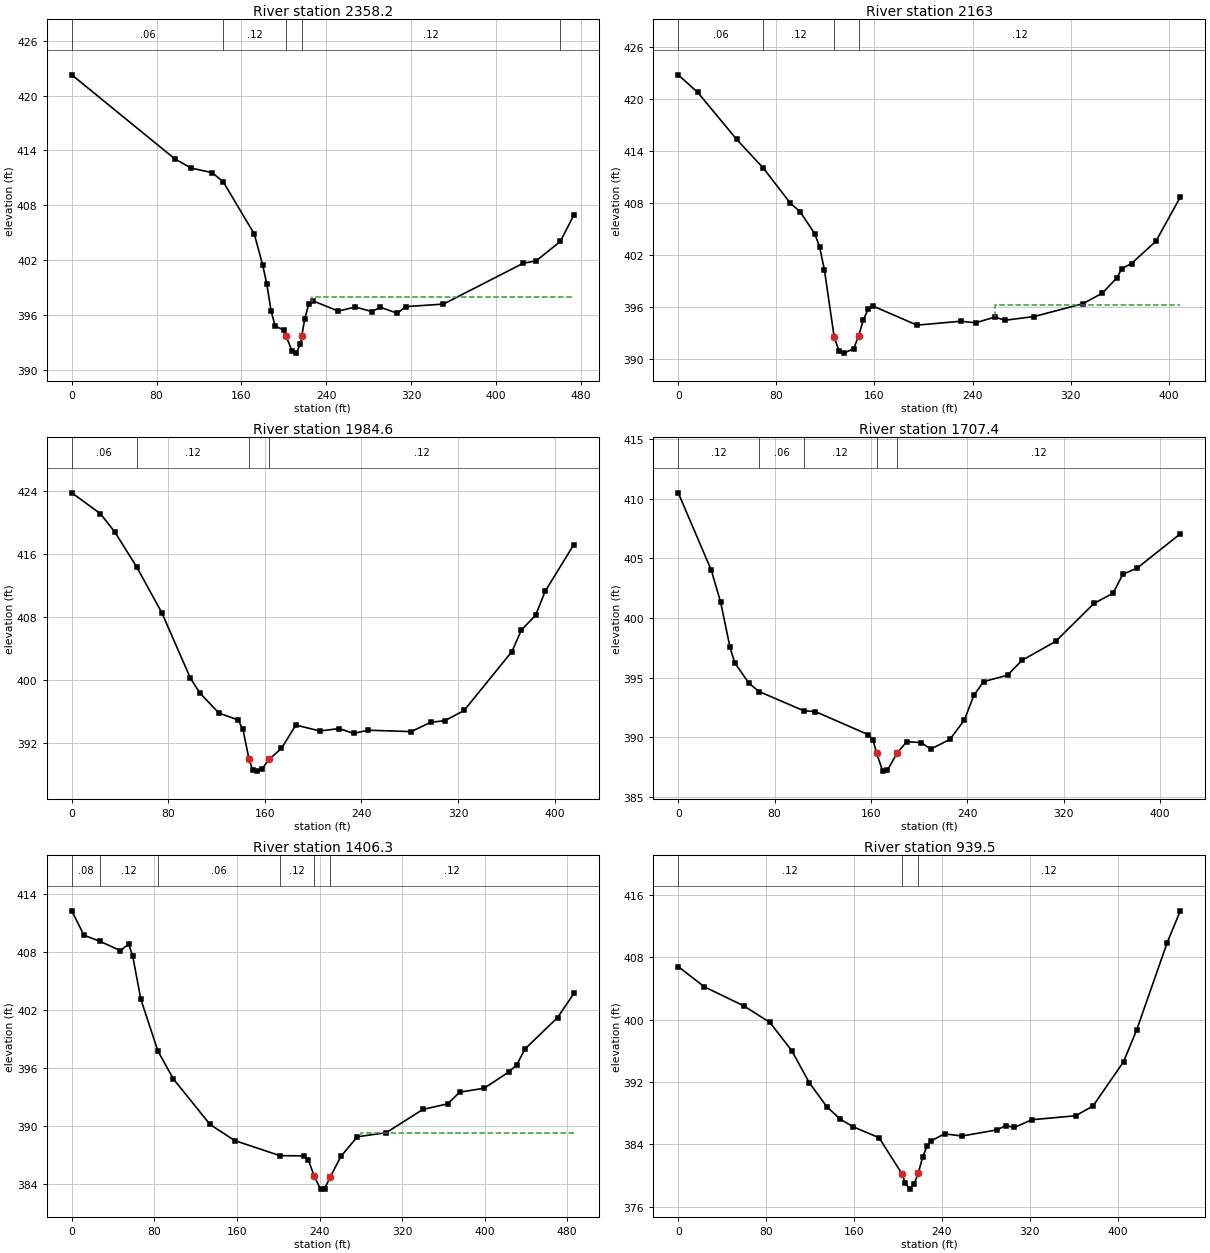
Type RM Length L Ch R = 1 ,2358.2  ,192.5,195.2,195.8
XS GIS Cut Line= 3
     2377463.013       417273.45     2377522.692      417177.964
     2377875.339      417100.924
#Sta/Elev= 30
       0  422.27    97.1  413.08   112.6  412.06   132.4  411.56  142.85410.5556
   172.1  404.86     180  401.49     184  399.35     188  396.43   191.9  394.74
   199.9  394.35   202.2393.6469   207.8  392.03   211.8   391.8   215.7  392.83
  216.93393.6589   219.7  395.52   223.7  397.22   227.6  397.52   251.4   396.4
   267.3  396.85   283.2  396.35   291.1  396.83     307  396.16   314.9  396.89
   350.6  397.17     426  401.65   437.9  401.89  460.89 404.029   473.6  406.92
#Mann= 5 ,-1 , 0
       0     .06       0  142.85     .12       0   202.2    .045       0
  216.93     .12       0  460.89    .016       0
#XS Ineff= 2 , 0
                          226.52          397.98
Permanent Ineff=
       F       F
Bank Sta=202.2,216.93
XS Rating Curve= 0 ,0
Exp/Cntr=0.3,0.1

Type RM Length L Ch R = 1 ,2163    ,179.6,178.4,176.3
XS GIS Cut Line= 2
     2377494.046      417366.288     2377898.994      417306.392
#Sta/Elev= 30
       0  422.81    15.9  420.78    47.7  415.35   69.39412.0512    91.4     408
    99.4  407.01   111.3  404.48   115.2  402.99   119.2   400.3   127.2  392.52
   131.2  390.91   135.1   390.7   143.1  391.21     147  392.67     151  394.53
     155  395.83     159  396.12   194.7  393.93   230.5  394.38   242.4   394.2
   258.3  394.86   266.3  394.49   290.1  394.92   329.9   396.4   345.8  397.62
   357.7  399.39   361.7  400.44   369.6  401.04   389.5  403.61   409.4   408.7
#Mann= 4 ,-1 , 0
       0     .06       0   69.39     .12       0   127.2    .045       0
     147     .12       0
#XS Ineff= 2 , 0
                             258          396.21
Permanent Ineff=
       F       F
Bank Sta=127.2,147
XS Rating Curve= 0 ,0
Exp/Cntr=0.3,0.1

Type RM Length L Ch R = 1 ,1984.6  ,270.8,277.2,283
XS GIS Cut Line= 4
     2377511.841      417528.441     2377625.773      417528.441
     2377823.256      417480.698     2377921.997      417476.358
#Sta/Elev= 30
       0  423.78    23.6  421.15    35.4  418.87   53.88414.3559    74.6  408.57
    98.2   400.3   106.1   398.4   121.9  395.85   137.8  394.98   141.8  393.77
  146.81390.0191   149.8  388.65   153.8  388.49   157.8  388.81  163.47389.9781
   173.7  391.38   185.6  394.33   205.6  393.58   221.5  393.89   233.4  393.27
   245.4  393.68   281.2   393.5   297.2  394.68   309.1  394.89     325  396.18
   364.6  403.65   372.4  406.37   384.3  408.28   392.2  411.31   415.9  417.22
#Mann= 4 ,-1 , 0
       0     .06       0   53.88     .12       0  146.81    .045       0
  163.47     .12       0
Bank Sta=146.81,163.47
XS Rating Curve= 0 ,0
Exp/Cntr=0.3,0.1

Type RM Length L Ch R = 1 ,1707.4  ,301,301,298.3
XS GIS Cut Line= 3
     2377503.161      417745.455     2377582.371      417779.092
     2377913.317      417784.517
#Sta/Elev= 30
       0   410.5    27.4  404.02    35.2  401.33      43  397.54    46.9  396.24
    58.7  394.53    67.1393.8292  104.15392.2208     114  392.14   157.8  390.21
   161.8  389.76  164.73388.6698   169.8  387.15   173.8  387.24   181.8  388.67
   189.7  389.61   201.7  389.55   209.7     389   225.6  389.81   237.6  391.43
   245.6  393.52   253.6  394.66   273.5   395.2   285.4  396.44   313.4  398.03
   345.3  401.22   361.2  402.08   369.2  403.66   381.2  404.19     417  407.06
#Mann= 5 ,-1 , 0
       0     .12       0    67.1     .06       0  104.15     .12       0
  164.73    .045       0   181.8     .12       0
Bank Sta=164.73,181.8
XS Rating Curve= 0 ,0
Exp/Cntr=0.3,0.1

Type RM Length L Ch R = 1 ,1406.3  ,465.4,466.8,467.9
XS GIS Cut Line= 4
     2377463.013      418113.294     2377586.711       418052.53
     2377816.746      418043.849     2377928.508      418004.787
#Sta/Elev= 30
       0  412.23    11.8  409.71   27.08409.0951    47.2  408.12    55.1   408.8
    59.1  407.52    66.9  403.11   83.46 397.751    98.4  394.88   133.9  390.18
   157.7  388.52  201.56 386.958   225.1  386.93   229.1  386.54  234.97384.8037
     241   383.5     245  383.56  250.59384.7932   260.8  386.89   276.7  388.91
   304.5  389.32   340.2  391.73     364   392.3   375.9  393.51   399.6  393.92
   423.3  395.59   431.2  396.35     439  397.96   470.6  401.21   486.4   403.7
#Mann= 6 ,-1 , 0
       0     .08       0   27.08     .12       0   83.46     .06       0
  201.56     .12       0  234.97    .045       0  250.59     .12       0
#XS Ineff= 2 , 0
                          280.19          389.28
Permanent Ineff=
       F       F
Bank Sta=234.97,250.59
XS Rating Curve= 0 ,0
Exp/Cntr=0.3,0.1

Type RM Length L Ch R = 1 ,939.5   ,367.1,369.1,370.4
XS GIS Cut Line= 2
     2377514.011      418432.304     2377970.826      418419.283
#Sta/Elev= 30
       0  406.83    23.8  404.23    59.6  401.79    83.4  399.66   103.3  396.04
   119.2  391.94   135.1  388.86     147  387.28     159  386.27   182.8  384.85
   203.9  380.16   206.6  379.05   210.6  378.25   214.6  378.85   218.6  380.37
   222.5  382.37   226.5   383.8   230.5  384.47   242.4  385.35   258.3  385.07
   290.1  385.86     298   386.4     306  386.17   321.9  387.16   361.6  387.67
   377.5  388.92   405.3   394.6   417.3   398.7   445.1  409.92     457  413.99
#Mann= 3 ,-1 , 0
       0     .12       0   203.9    .045       0   218.6     .12       0
Bank Sta=203.9,218.6
XS Rating Curve= 0 ,0
Exp/Cntr=0.3,0.1

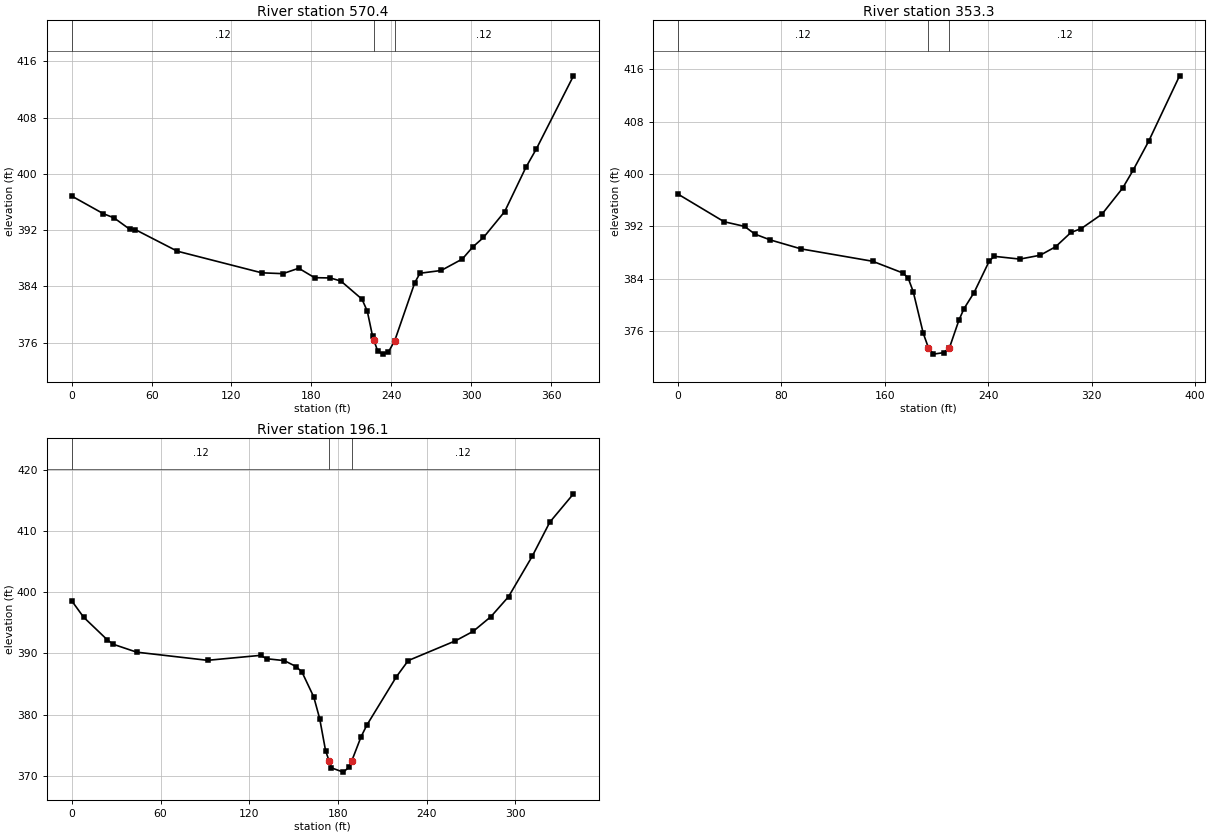
Type RM Length L Ch R = 1 ,570.4   ,226.1,217.1,207.2
XS GIS Cut Line= 3
     2377637.709      418713.337     2377935.018      418710.082
     2378010.973       418686.21
#Sta/Elev= 30
       0  396.84    23.8  394.33    31.7  393.75    43.6  392.12    47.6  392.09
    79.3  389.01   142.7  385.94   158.6  385.82   170.5  386.59   182.4  385.25
   194.2  385.21   202.2  384.77     218   382.2     222   380.5     226  376.91
  226.97376.3815   229.9  374.77   233.9  374.39   237.9  374.71  242.55376.2625
   257.7  384.55   261.6  385.88   277.5  386.27   293.4   387.9   301.3  389.62
   309.3  390.96   325.2  394.63   341.1   400.9   349.1  403.57   376.9  413.92
#Mann= 3 ,-1 , 0
       0     .12       0  226.97    .045       0  242.55     .12       0
Bank Sta=226.97,242.55
XS Rating Curve= 0 ,0
Exp/Cntr=0.3,0.1

Type RM Length L Ch R = 1 ,353.3   ,158.3,157.3,156.5
XS GIS Cut Line= 4
     2377686.537      418957.478     2377801.555      418963.988
      2377958.89      418892.373     2378057.631      418877.182
#Sta/Elev= 30
       0  396.92    35.8  392.68    51.6  391.97    59.6  390.79    71.5   389.9
    95.3  388.53   150.6  386.64   174.1  384.84   178.1  384.08     182  382.01
   189.8  375.62   193.8   373.4   197.7  372.44   205.6  372.67  209.99373.3799
   217.4  377.65   221.3  379.39   229.1  381.86   240.9   386.7   244.8  387.39
   264.5  386.97   280.2  387.56   292.1  388.85     304  391.04     312  391.64
     328  393.84     344  397.83     352  400.53     364  404.95     388  414.99
#Mann= 3 ,-1 , 0
       0     .12       0   193.8    .045       0  209.99     .12       0
Bank Sta=193.8,209.99
XS Rating Curve= 0 ,0
Exp/Cntr=0.3,0.1

Type RM Length L Ch R = 1 ,196.1   ,198.1,196.1,193.9
XS GIS Cut Line= 2
     2377759.237      419153.875     2378060.886       418998.71
#Sta/Elev= 30
       0  398.58       8  395.92    23.9  392.25    27.9  391.51    43.9  390.21
    91.8  388.88   127.7  389.69   131.7  389.14   143.7  388.83   151.6  387.87
   155.6  386.99   163.6  382.91   167.6  379.38   171.6  374.14  174.07372.4035
   175.6  371.33   183.6  370.64   187.6  371.48  189.17372.3879   195.6  376.41
   199.5  378.31   219.5  386.21   227.5  388.84   259.4  392.06   271.4  393.61
   283.4  396.01   295.3  399.26   311.3  405.85   323.2  411.42   339.2  416.04
#Mann= 3 ,-1 , 0
       0     .12       0  174.07    .045       0  189.17     .12       0
Bank Sta=174.07,189.17
XS Rating Curve= 0 ,0
Exp/Cntr=0.3,0.1

Chan Stop Cuts=-1
Use User Specified Reach Order=0
Composite Channel Slope=5